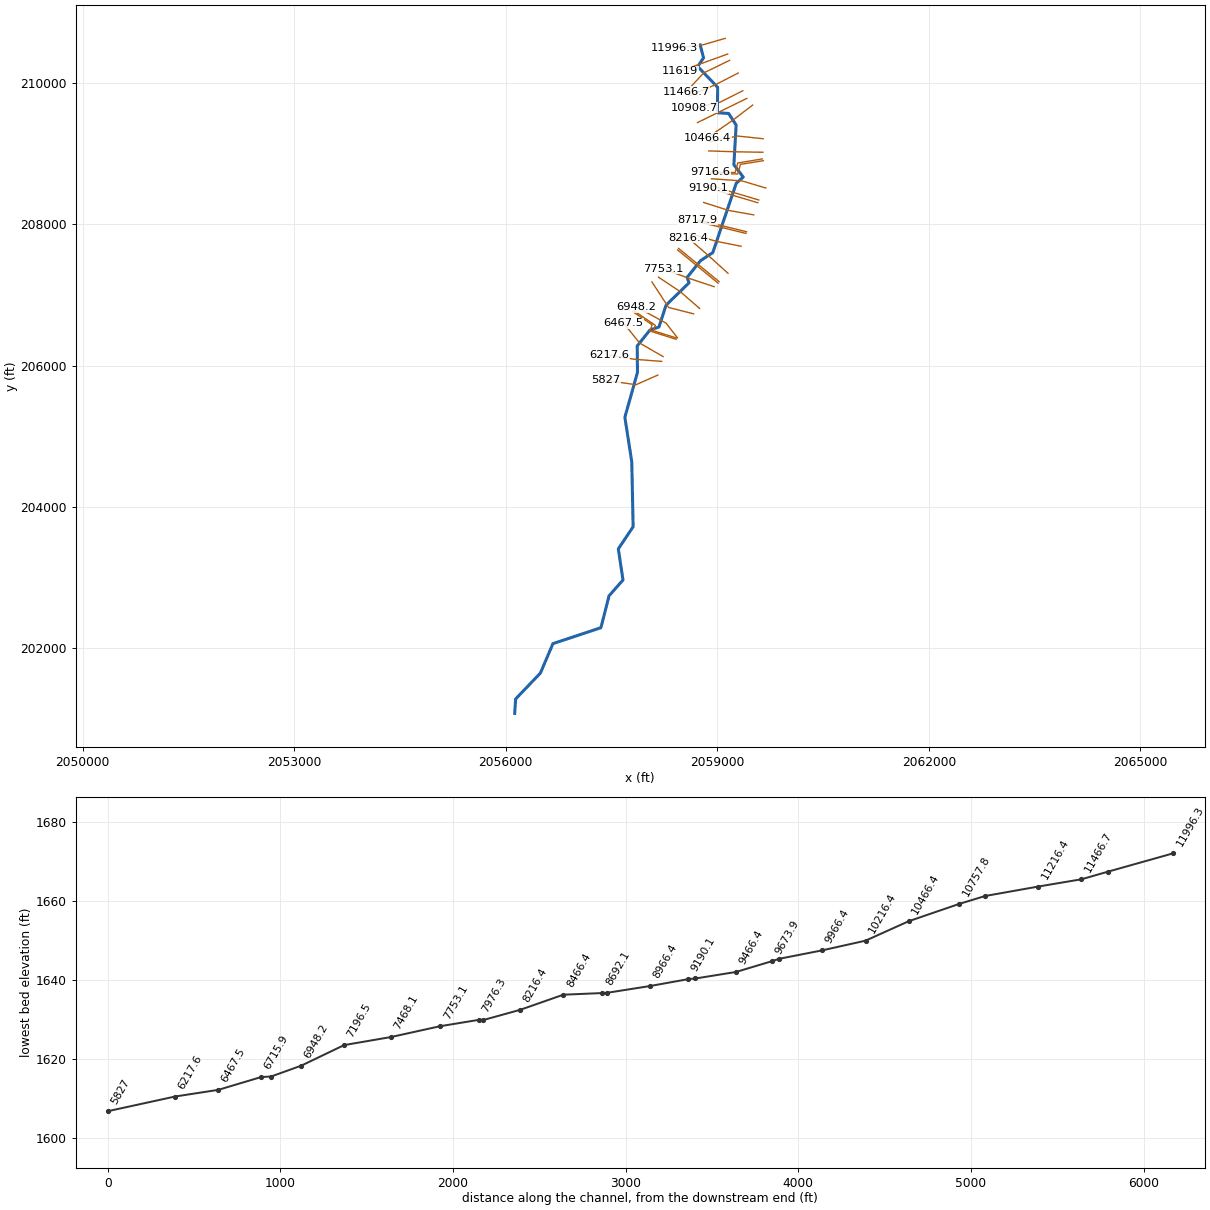
--- INDIANDFT.prj (project) ---

Proj Title=INDIANDFT
Current Plan=p01
Default Exp/Contr=0,0
English Units
Geom File=g01
Flow File=f01
Plan File=p01
BEGIN DESCRIPTION:
END DESCRIPTION:
DSS Export Rating Curves= 0
DSS Export Rating Curve Sorted= 0
DSS Export Volume Flow Curves= 0
DXF OffsetX= 0
DXF OffsetY= 0
DXF ScaleX= 0
DXF ScaleY= 0

--- INDIANDFT.p01 (plan) ---

Plan Title=Floodplain
Program Version=4.00
Geom File=g01
Flow File=f01
K Sum by GR=0
Std Step Tol=0.01
Critical Tol=0.01
Num of Std Step Trials=20
Max Error Tol=0.3
Flow Tol Ratio=0.001
Split Flow NTrial=30
Split Flow Tol=0.02
Split Flow Ratio=0.02
Log Output Level=0
Friction Slope Method=1
Unsteady Friction Slope Method=2
Unsteady Bridges Friction Slope Method=1
Global Log Level=0
CheckData=False
Run HTab=0
Run UNet=0
Run PostProcess=0
UNET Theta=0
UNET Theta Warmup=0
UNET ZTol=0
UNET ZSATol=0
UNET MxIter=0
UNET MaxInSteps=0
UNET DtIC=0
UNET DtMin=0
UNET MaxCRTS=0
UNET WFStab=0
UNET SFStab=0
UNET WFX=0
UNET SFX=0
UNET DSS MLevel=0
UNET DZMax Abort=0
UNET Convert EG Bridges=0
UNET Use Existing IB Tables=0
UNET Froude Limit=0
UNET Froude Power=0
Write IC File=0
Echo Input=False
Echo Output=False
Write Detailed=0

--- INDIANDFT.f01 (steady flow) ---

Flow Title=2010 USGS WV Regression Equation
Program Version=4.00
Number of Profiles=1
Profile Names=P100yr
River Rch & RM=INDIANDFT,Main      ,11996.3
568.4451
River Rch & RM=INDIANDFT,Main      ,10757.8
622.1695
River Rch & RM=INDIANDFT,Main      ,9716.6
683.2126
River Rch & RM=INDIANDFT,Main      ,8966.4
711.6473
River Rch & RM=INDIANDFT,Main      ,8216.4
 790.966
River Rch & RM=INDIANDFT,Main      ,8002
800.9835
River Rch & RM=INDIANDFT,Main      ,3968.9
886.2039
River Rch & RM=INDIANDFT,Main      ,78.7
992.7471
River Rch & RM=INDIANDFT,Main      ,78.7
973.9188
Boundary for River Rch & Prof#=INDIANDFT,Main      ,1
Up Type=0
Dn Type=3
Dn Slope=0.006423

--- INDIANDFT.g01 (geometry) ---

Geom Title=LiDAR
Program Version=4.10

River Reach=INDIANDFT       ,Main
Reach XY= 30
     2058757.061      210544.618     2058805.238      210361.458
     2058722.339      210238.194     2059005.325      209943.489
     2059001.853      209583.246     2059160.707       209572.83
     2059267.478      209409.201      2059235.36      208845.399
     2059368.173      208671.788      2059268.78       208583.68
     2058936.749      207601.476     2058762.704      207486.458
     2058571.661      207248.015     2058600.377      207173.958
     2058273.554      206855.382     2058172.426      206546.354
     2058044.116      206502.417       2057864.7      206278.993
     2057868.172      205903.125     2057689.353      205267.274
     2057787.443      204634.462      2057806.54      203715.191
     2057596.471      203402.691     2057662.752      202960.856
      2057465.27      202737.332     2057349.818      202285.075
     2056669.436      202059.409     2056490.964      201641.354
      2056140.27      201274.687     2056127.083      201070.803

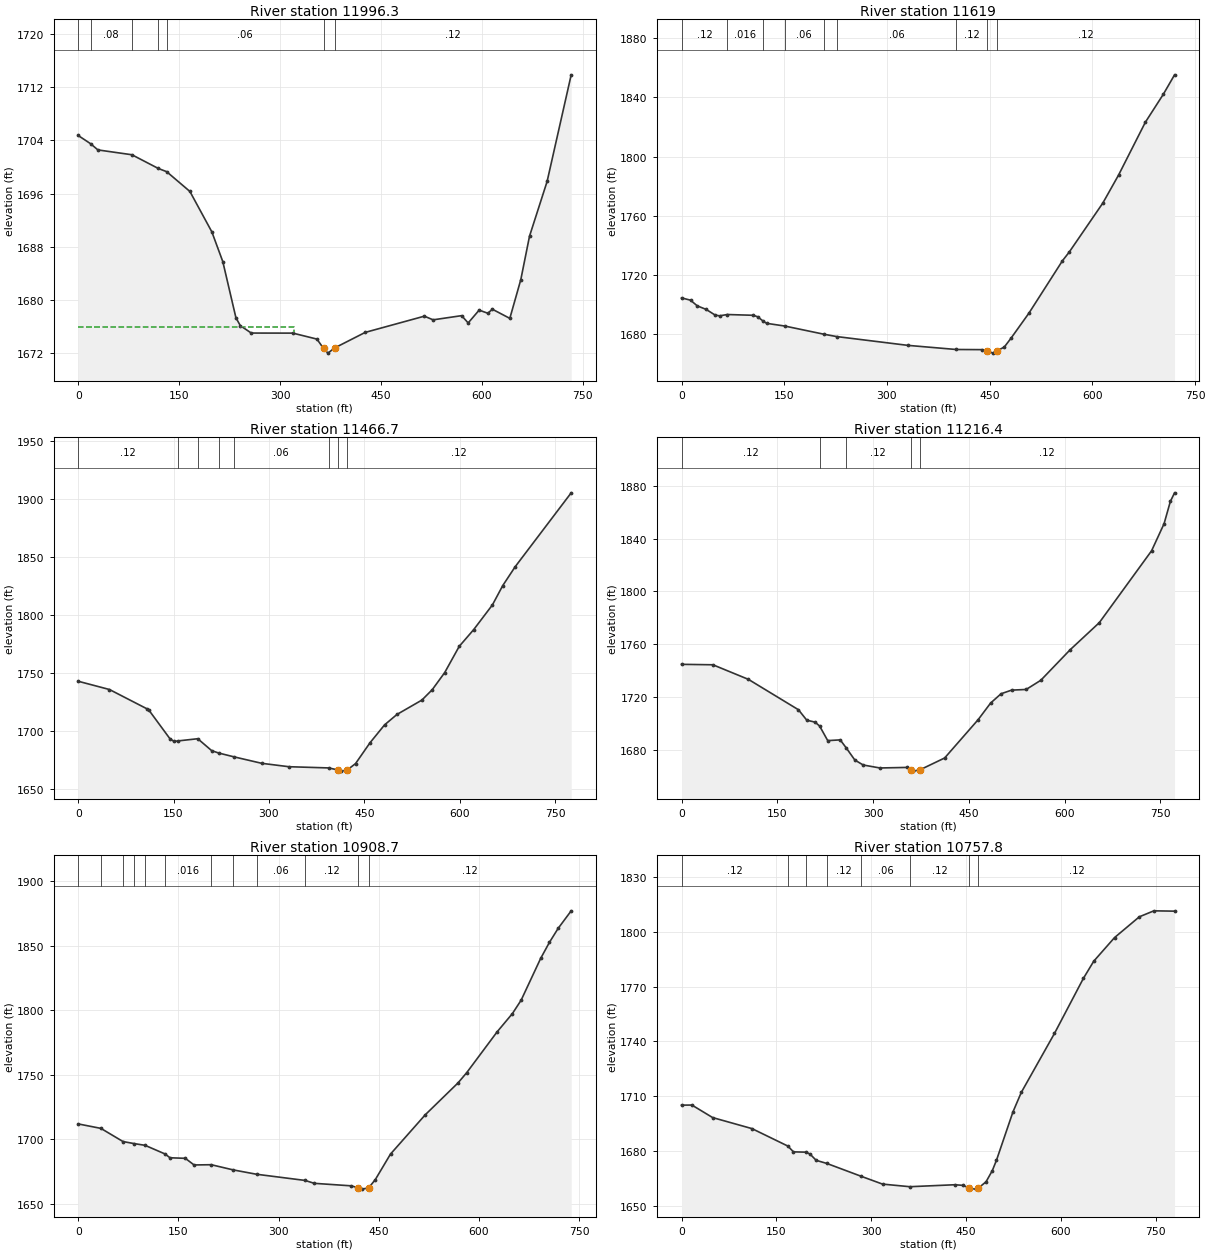
Type RM Length L Ch R = 1 ,11996.3 ,349.7,377.2,360.9
XS GIS Cut Line= 3
     2059112.671      210637.576     2058759.398      210535.006
     2058395.862      210505.359
#Sta/Elev= 30
       0 1704.75   18.321703.521    29.3 1702.58   79.841701.852  119.111699.787
  131.451699.307     166 1696.33   198.6 1690.25   214.9 1685.77   234.4 1677.32
   240.9 1676.14   257.2 1675.02     319 1675.01   354.8 1674.11   364.6  1672.7
   371.1    1672   380.9 1672.77   426.5 1675.12   514.4 1677.56   527.4 1677.01
   569.8 1677.64   579.5 1676.54   595.8 1678.47   608.8    1678   615.4 1678.61
   641.4 1677.23   657.7 1683.05   670.7 1689.61   696.8 1697.83   732.6 1713.88
#Mann= 7 ,-1 , 0
       0    .016       0   18.32     .08       0   79.84     .06       0
  119.11     .08       0  131.45     .06       0   364.6    .045       0
   380.9     .12       0
#XS Ineff= 2 , 0
          320.47 1675.94
Permanent Ineff=
       F       F
Bank Sta=364.6,380.9
XS Rating Curve= 0 ,0
Exp/Cntr=0.3,0.1

Type RM Length L Ch R = 1 ,11619   ,148.3,152.3,162.4
XS GIS Cut Line= 2
     2059148.254      210415.532     2058471.171       210170.74
#Sta/Elev= 30
       0 1704.64    13.1 1703.11    22.9 1699.28      36 1696.86    49.1 1693.04
    55.6 1692.54   66.821693.429   104.7 1692.91   111.3  1691.9  119.361688.882
   124.4 1687.47  150.761685.653  207.431680.172  226.491678.552   330.5 1672.61
  401.031669.825   438.5 1669.72   446.8 1668.74   454.9 1667.37  460.061668.813
   471.3 1671.45   481.1 1677.41   507.3 1694.34   556.3 1729.73   566.2  1735.6
   615.2 1768.64   638.2 1787.54   677.4 1823.26   703.6  1842.1     720 1855.22
#Mann= 9 ,-1 , 0
       0     .12       0   66.82    .016       0  119.36     .08       0
  150.76     .06       0  207.43     .12       0  226.49     .06       0
  401.03     .12       0   446.8    .045       0  460.06     .12       0
Bank Sta=446.8,460.06
XS Rating Curve= 0 ,0
Exp/Cntr=0.3,0.1

Type RM Length L Ch R = 1 ,11466.7 ,249.9,250.4,239.5
XS GIS Cut Line= 3
     2059175.613      210326.039     2058806.842      210146.842
     2058557.491      209879.838
#Sta/Elev= 30
       0 1742.87    49.2 1735.75   108.2 1719.12   111.5 1717.78   144.3 1693.33
   150.9    1691  156.791691.472  188.051693.367   209.9 1683.11  220.891681.054
  244.391677.839   288.6 1672.19   331.3 1669.26  394.341668.209  408.471666.439
   413.3 1665.46     423 1666.42   436.1 1671.91   458.9 1689.88   481.8 1705.29
   501.3 1714.28   540.5 1726.65   556.8 1735.61   576.4 1750.36   599.2 1772.91
     622 1787.37   651.4 1808.61   667.7  1825.3   687.3 1841.58   775.3 1905.16
#Mann= 8 ,-1 , 0
       0     .12       0  156.79    .016       0  188.05     .08       0
  220.89     .12       0  244.39     .06       0  394.34     .12       0
  408.47    .045       0     423     .12       0
Bank Sta=408.47,423
XS Rating Curve= 0 ,0
Exp/Cntr=0.3,0.1

Type RM Length L Ch R = 1 ,11216.4 ,312.7,307.7,296.8
XS GIS Cut Line= 3
     2059297.235      210146.361     2058971.385      209978.946
     2058596.786      209822.274
#Sta/Elev= 30
       0  1744.7    49.1 1744.36   104.7  1733.3   183.2  1710.2   196.2 1702.29
   209.3 1700.79  216.361697.811     229 1686.79   248.6 1687.34  257.661681.477
   271.5 1672.04   284.6 1668.27   310.7 1666.02   353.3 1666.43   358.8 1664.65
   363.1 1663.62   373.8 1664.68   412.2  1673.6   464.6 1702.64   484.2  1715.3
   500.6 1722.36     517 1725.11   539.9 1725.62   562.8 1732.57   608.7 1755.71
   654.5 1776.34   736.4 1830.91     756  1851.5   765.8 1868.34   772.4 1874.91
#Mann= 5 ,-1 , 0
       0     .12       0  216.36    .016       0  257.66     .12       0
   358.8    .045       0   373.8     .12       0
Bank Sta=358.8,373.8
XS Rating Curve= 0 ,0
Exp/Cntr=0.3,0.1

Type RM Length L Ch R = 1 ,10908.7 ,145.6,150.8,151.7
XS GIS Cut Line= 3
     2059361.796      209894.698     2059037.143      209731.504
     2058670.823      209651.643
#Sta/Elev= 30
       0 1711.83      341708.372   67.061698.165   83.241696.607  100.121695.227
  130.13  1688.5   137.5 1685.56   160.4 1685.14   173.5 1679.99   199.31680.171
  232.361676.123  267.151672.769  339.931667.963   353.5 1665.73     409 1663.78
   419.1 1662.26   425.3 1661.23   435.1 1662.32   444.9 1668.58   467.7 1688.43
   519.8 1718.95   568.8 1743.65   581.8 1751.58   627.4  1783.3   650.3 1797.48
   663.3 1807.82   692.6  1840.3   705.7 1852.72   718.7 1863.53   738.3 1877.19
#Mann= 12 ,-1 , 0
       0     .12       0      34     .06       0   67.06     .12       0
   83.24     .08       0  100.12     .12       0  130.13    .016       0
   199.3     .08       0  232.36     .12       0  267.15     .06       0
  339.93     .12       0   419.1    .045       0   435.1     .12       0
Bank Sta=419.1,435.1
XS Rating Curve= 0 ,0
Exp/Cntr=0.3,0.1

Type RM Length L Ch R = 1 ,10757.8 ,285.6,291.5,292.7
XS GIS Cut Line= 2
     2059419.743      209786.444     2058719.222      209443.562
#Sta/Elev= 30
       0 1705.15    16.4 1705.19    49.2 1698.34   111.4 1692.31  168.161682.769
     177  1679.6  196.99 1679.43   203.2  1678.4     213 1674.96  229.881673.259
  284.621666.181   317.9 1661.97  361.131660.543   432.6 1661.62   445.7 1661.26
   455.5 1659.68   465.3 1659.22  469.521659.792   481.7 1663.24   491.6 1669.34
   498.1 1674.93   524.3 1701.48   537.4 1712.08   589.9 1744.34   635.7 1774.48
   652.1 1783.87   684.9 1796.74   724.2 1808.14   747.2  1811.4   779.9 1811.22
#Mann= 8 ,-1 , 0
       0     .12       0  168.16    .016       0  196.99     .08       0
  229.88     .12       0  284.62     .06       0  361.13     .12       0
   455.5    .045       0  469.52     .12       0
Bank Sta=455.5,469.52
XS Rating Curve= 0 ,0
Exp/Cntr=0.3,0.1

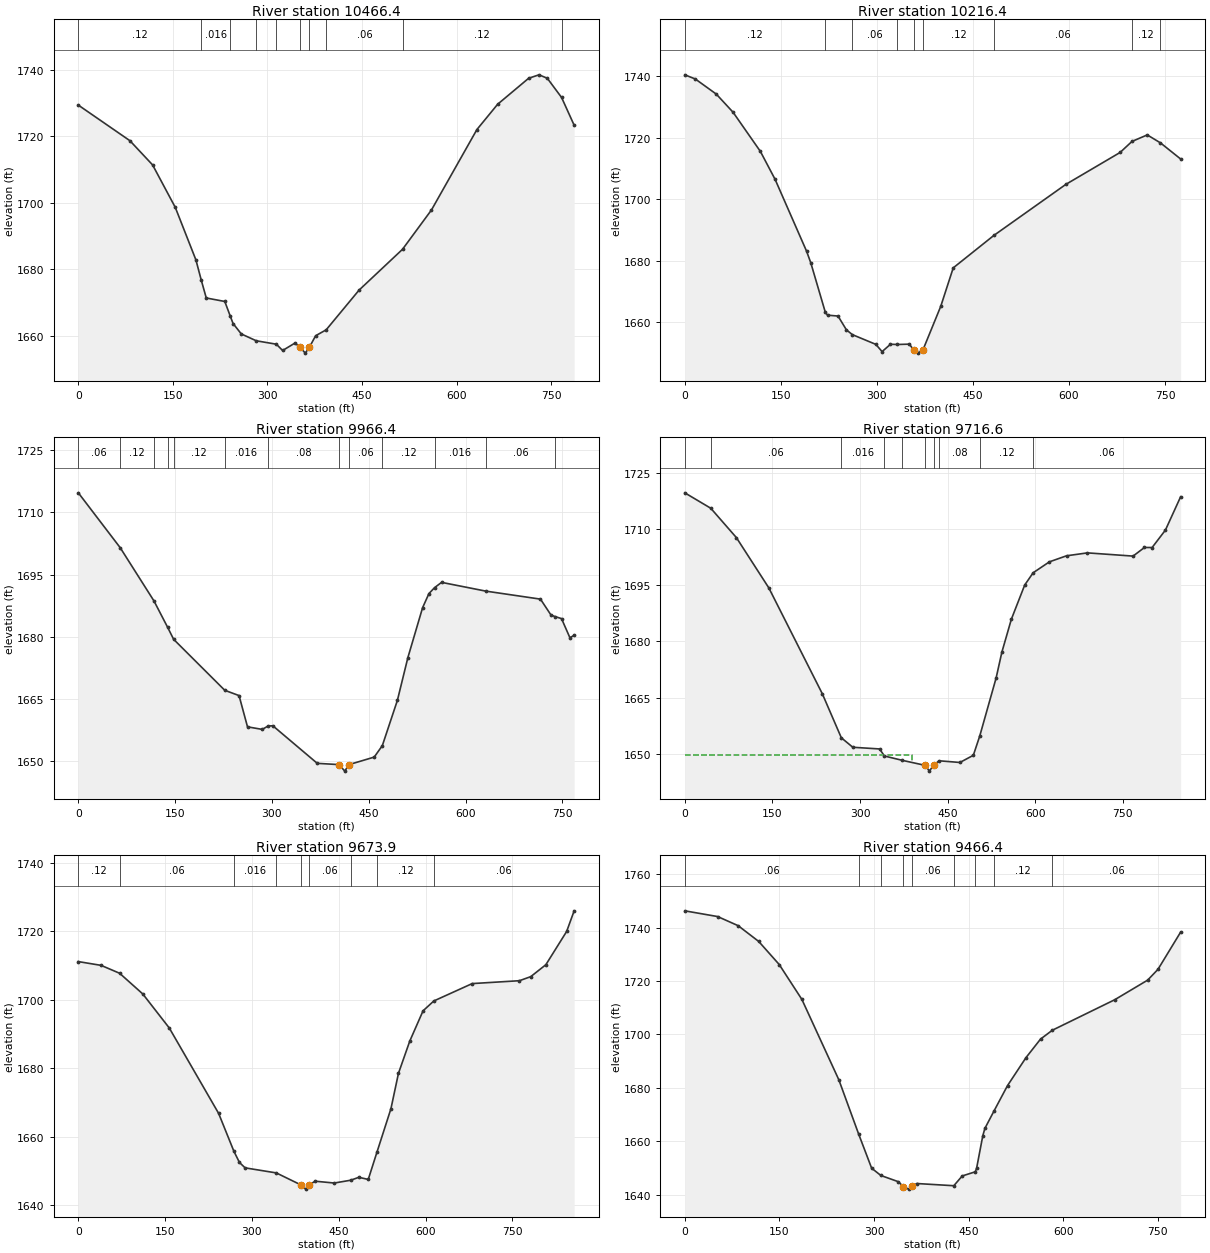
Type RM Length L Ch R = 1 ,10466.4 ,266.4,250,240.9
XS GIS Cut Line= 3
     2059501.292      209691.624     2059217.761      209475.218
     2058863.431       209232.02
#Sta/Elev= 30
       0 1729.37    81.8 1718.68   117.8  1711.4   153.8 1698.63   186.5 1682.86
  194.921676.828   202.9 1671.43   232.3 1670.38   240.61666.164   245.4 1663.76
   258.5 1660.62  282.231658.567  314.09 1657.54     324 1655.65   343.6 1657.88
  351.611656.616     360 1654.86   366.5 1656.64   376.4 1660.09  393.111661.864
   445.3  1673.8  514.171686.053   560.1 1697.87   632.2 1722.04   665.1 1729.64
   714.3 1737.45   730.7 1738.47   743.8 1737.44  766.451731.668   786.4 1723.32
#Mann= 10 ,-1 , 0
       0     .12       0  194.92    .016       0   240.6     .12       0
  282.23     .06       0  314.09     .12       0  351.61    .045       0
   366.5     .12       0  393.11     .06       0  514.17     .12       0
  766.45     .08       0
Bank Sta=351.61,366.5
XS Rating Curve= 0 ,0
Exp/Cntr=0.3,0.1

Type RM Length L Ch R = 1 ,10216.4 ,246.2,250,242.6
XS GIS Cut Line= 3
     2059650.773      209214.496     2059288.993      209253.124
     2058886.987      209170.182
#Sta/Elev= 30
       0 1740.39    16.4 1739.04    49.2 1734.12    75.4 1728.22     118 1715.51
     141 1706.42   190.1  1683.1   196.7 1679.33  219.491663.182   222.9 1662.28
   239.3 1661.99   252.4  1657.5  261.731655.944   298.3 1652.79   308.1 1650.43
   321.2 1652.82     3321652.747   350.7 1652.86   357.3    1651   363.8 1649.94
  371.981651.021   399.7 1665.15   419.2 1677.65  482.591688.182   595.1 1704.79
   679.8 1715.16  698.351718.745   722.2 1720.86  742.741718.285   774.3 1713.04
#Mann= 9 ,-1 , 0
       0     .12       0  219.49    .016       0  261.73     .06       0
     332     .12       0   357.3    .045       0  371.98     .12       0
  482.59     .06       0  698.35     .12       0  742.74    .016       0
Bank Sta=357.3,371.98
XS Rating Curve= 0 ,0
Exp/Cntr=0.3,0.1

Type RM Length L Ch R = 1 ,9966.4  ,219.2,249.8,279
XS GIS Cut Line= 3
     2059646.924      209022.921     2059234.204      209030.263
      2058879.03      209041.891
#Sta/Elev= 30
       0 1714.73    64.91701.468  117.221688.603  138.261682.272  147.651679.343
  226.891667.027     249 1665.75   262.1  1658.2     285 1657.58  294.091658.411
   301.4 1658.45   370.2 1649.38  404.011649.073   412.8  1647.5   419.3 1649.07
   458.4 1650.89  470.991653.657   494.3 1664.58   510.6 1674.94   533.4 1686.99
   543.2 1690.39  551.921691.823   562.8  1693.1  631.14 1690.99     716 1689.05
   732.3 1685.21  738.421684.842   748.6 1684.35   761.6 1679.73   768.2 1680.31
#Mann= 13 ,-1 , 0
       0     .06       0    64.9     .12       0  117.22    .016       0
  138.26     .06       0  147.65     .12       0  226.89    .016       0
  294.09     .08       0  404.01    .045       0   419.3     .06       0
  470.99     .12       0  551.92    .016       0  631.14     .06       0
  738.42    .016       0
Bank Sta=404.01,419.3
XS Rating Curve= 0 ,0
Exp/Cntr=0.3,0.1

Type RM Length L Ch R = 1 ,9716.6  ,42.4,42.6,42.9
XS GIS Cut Line= 4
     2059639.081       208928.48     2059290.774      208870.972
     2059252.797      208735.338     2058897.979      208738.593
#Sta/Elev= 30
       0 1719.65   44.471715.533    88.3  1707.7   143.8 1694.28   235.4 1666.01
  267.941654.257   287.6 1651.73   333.4 1651.28  341.721649.393  371.681648.262
     412 1646.88   418.5 1645.36  426.011646.939  435.181648.122   470.9 1647.67
   493.9 1649.59   504.91654.755   532.9 1670.23   542.7  1677.1     559 1685.92
   581.8 1695.03  596.231698.307   624.1 1701.23   653.4 1702.84   689.2 1703.62
   767.3 1702.76   786.8 1705.06   799.9 1705.05   822.7 1709.71   848.7  1718.6
#Mann= 10 ,-1 , 0
       0     .12       0   44.47     .06       0  267.94    .016       0
  341.72     .08       0  371.68    .016       0     412    .045       0
  426.01     .12       0  435.18     .08       0   504.9     .12       0
  596.23     .06       0
#XS Ineff= 2 , 0
          388.92 1649.79
Permanent Ineff=
       F       F
Bank Sta=412,426.01
XS Rating Curve= 0 ,0
Exp/Cntr=0.3,0.1

Type RM Length L Ch R = 1 ,9673.9  ,243.7,207.6,175.8
XS GIS Cut Line= 4
     2059652.102      208903.524     2059328.752       208851.44
     2059290.774      208715.807     2058902.319      208717.977
#Sta/Elev= 30
       0 1711.17    39.3 1710.07   71.29 1707.77   111.4 1701.72   157.2 1691.78
   242.4 1666.87  268.841655.796   278.4 1652.54   288.2 1650.96  342.091649.484
  384.65 1645.98     393 1644.75  398.711646.011   409.4 1647.06   442.2 1646.53
  470.661647.348   484.7  1648.2     501 1647.58  516.291655.679   540.2 1668.23
   553.2 1678.56   572.8 1687.99   595.7  1696.8  614.32 1699.68   680.6 1704.75
   762.2 1705.59   781.8 1706.78   807.9 1710.26   843.8 1719.96   856.8 1725.99
#Mann= 9 ,-1 , 0
       0     .12       0   71.29     .06       0  268.84    .016       0
  342.09     .06       0  384.65    .045       0  398.71     .06       0
  470.66    .016       0  516.29     .12       0  614.32     .06       0
Bank Sta=384.65,398.71
XS Rating Curve= 0 ,0
Exp/Cntr=0.3,0.1

Type RM Length L Ch R = 1 ,9466.4  ,232.5,234.8,229.5
XS GIS Cut Line= 3
     2059688.251      208516.077     2059351.505      208617.097
     2058918.143      208647.436
#Sta/Elev= 30
       0 1746.34    52.1 1744.19    84.6 1740.77   117.2 1734.86   149.7 1726.21
   185.6 1713.14   244.2    1683  275.741662.576   296.2 1649.87  310.811647.148
   338.6  1644.8  346.661642.926   354.8 1642.03  359.731643.025   367.9 1644.13
  426.461643.306   439.8 1646.97  460.481648.525   462.6 1649.87   472.4 1662.03
   475.7 1664.79   490.11671.288   511.6 1680.84     541 1691.36   563.9 1698.26
  582.651701.588   681.5 1713.01   733.7 1720.36   750.1 1724.41     786 1738.35
#Mann= 9 ,-1 , 0
       0     .06       0  275.74     .12       0  310.81    .016       0
  346.66    .045       0  359.73     .06       0  426.46    .016       0
  460.48     .08       0   490.1     .12       0  582.65     .06       0
Bank Sta=346.66,359.73
XS Rating Curve= 0 ,0
Exp/Cntr=0.3,0.1

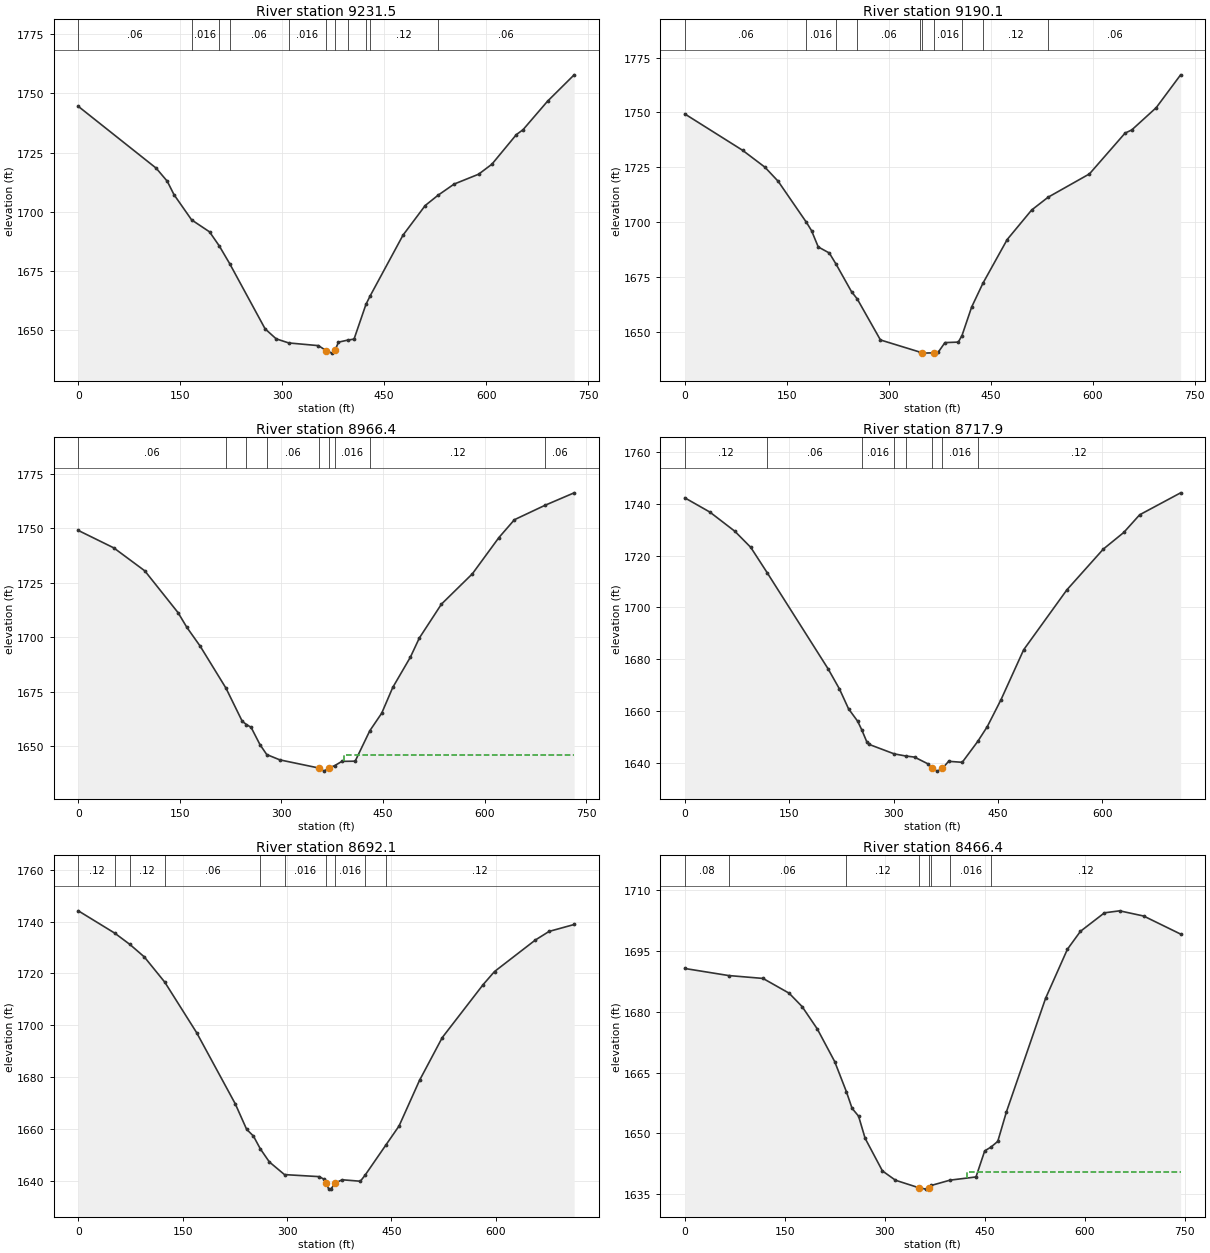
Type RM Length L Ch R = 1 ,9231.5  ,41.4,41.4,41.4
XS GIS Cut Line= 2
     2059589.275      208346.335     2058890.251      208554.789
#Sta/Elev= 30
       0 1744.54   114.5 1718.46   130.8 1712.95   140.7 1707.29  166.671696.624
     193 1691.58  207.361685.624  222.54 1678.21   274.8 1650.61   291.1  1646.4
  309.57 1644.68   353.3 1643.54  364.391641.476   372.9 1640.38   377.7 1641.62
   382.7 1645.01  396.381645.881   405.6  1646.3  423.131660.977  429.23  1664.5
   477.6 1690.17   510.3 1702.69  529.141707.023   552.8 1711.74   588.8  1715.9
   608.4 1720.13   644.4 1732.63   654.2 1734.69   690.2 1746.71   729.4 1757.86
#Mann= 11 ,-1 , 0
       0     .06       0  166.67    .016       0  207.36     .08       0
  222.54     .06       0  309.57    .016       0  364.39    .045       0
   377.7     .06       0  396.38    .016       0  423.13     .08       0
  429.23     .12       0  529.14     .06       0
Bank Sta=364.39,377.7
XS Rating Curve= 0 ,0
Exp/Cntr=0.3,0.1

Type RM Length L Ch R = 1 ,9190.1  ,220.8,223.7,222.7
XS GIS Cut Line= 2
     2059574.518      208307.707     2058875.494       208516.16
#Sta/Elev= 30
       0 1749.33      85 1732.75   117.8 1725.06   137.4 1718.59  178.921699.875
   186.4 1696.13   196.3 1688.66   212.6 1685.89  222.781680.665   245.3 1668.23
  253.611664.973   287.8 1646.23  346.081640.674  348.461640.402     350 1640.22
   366.4 1640.36   372.9 1640.68   382.7 1645.02   402.3 1645.25  407.731648.208
     422 1661.26  438.551672.083   474.3 1692.05   510.3 1705.52  534.491711.346
   595.3 1721.98   647.7 1740.59   657.5 1742.03   693.5 1752.19   729.4 1767.17
#Mann= 10 ,-1 , 0
       0     .06       0  178.92    .016       0  222.78     .08       0
  253.61     .06       0  346.08     .08       0  348.46    .045       0
   366.4    .016       0  407.73     .08       0  438.55     .12       0
  534.49     .06       0
Bank Sta=348.46,366.4
XS Rating Curve= 0 ,0
Exp/Cntr=0.3,0.1

Type RM Length L Ch R = 1 ,8966.4  ,246.2,248.5,249.1
XS GIS Cut Line= 3
     2059516.766      208135.364     2059159.405      208199.299
     2058807.606      208311.155
#Sta/Elev= 30
       0 1749.03    52.3 1741.04    98.1 1730.49   147.2  1711.3   160.3  1704.5
   179.9 1695.89  218.131676.526     242 1661.39  248.231659.869   255.1  1658.6
   268.2 1650.66  278.241646.074   297.6 1643.63   355.5 1639.87     363 1638.46
   370.5 1639.99  378.471640.963   389.2 1642.94   408.8 1643.03  430.421657.003
     448 1665.08   464.3  1676.9   490.4 1690.85   503.5 1699.58   536.2 1715.18
   581.9 1729.12   621.1 1745.78     644 1753.97  689.071760.579   732.2 1766.32
#Mann= 9 ,-1 , 0
       0     .06       0  218.13    .016       0  248.23     .08       0
  278.24     .06       0   355.5    .045       0   370.5     .06       0
  378.47    .016       0  430.42     .12       0  689.07     .06       0
#XS Ineff= 2 , 0
                          392.17         1645.93
Permanent Ineff=
       F       F
Bank Sta=355.5,370.5
XS Rating Curve= 0 ,0
Exp/Cntr=0.3,0.1

Type RM Length L Ch R = 1 ,8717.9  ,29.1,25.8,25.3
XS GIS Cut Line= 2
     2059415.557      207896.579     2058723.283       208065.85
#Sta/Elev= 30
       0 1742.36      36 1736.86    71.9 1729.45    94.8 1723.22  118.811713.252
     206 1676.27   222.3  1668.5   235.4 1660.82   248.4 1656.06  254.24 1652.79
   261.5 1648.14   264.8 1647.09  301.071643.408  317.32 1642.61   330.2 1642.17
   349.8 1639.52   355.3  1637.8   362.9 1636.75   370.3  1637.8   379.2 1640.54
   398.8 1640.16  421.031648.215   434.8 1653.95   454.4 1664.29   487.1 1683.65
   549.2  1706.8   601.5 1722.53   630.9 1728.96   653.8  1735.8   712.7 1744.29
#Mann= 8 ,-1 , 0
       0     .12       0  118.81     .06       0  254.24    .016       0
  301.07     .08       0  317.32    .016       0   355.3    .045       0
   370.3    .016       0  421.03     .12       0
Bank Sta=355.3,370.3
XS Rating Curve= 0 ,0
Exp/Cntr=0.3,0.1

Type RM Length L Ch R = 1 ,8692.1  ,222.9,225.8,224.7
XS GIS Cut Line= 2
     2059406.877      207872.708     2058714.602      208041.978
#Sta/Elev= 30
       0 1744.18    52.3 1735.57    74.11731.203    94.8 1726.39  124.261716.629
     170 1697.15   225.6 1669.63   241.9 1659.81   251.7 1657.19  261.661652.225
   274.6 1647.19  296.351642.309   346.5 1641.52   353.1  1640.5   356.3 1638.94
   359.6 1636.92   362.9  1636.7   369.4 1639.04   379.2 1640.31   405.4 1639.75
  412.091642.054   442.51653.902     461 1661.09   490.4 1678.69   523.1 1695.23
   581.9  1715.7   598.2 1720.73   657.1 1732.94   676.7 1736.23   712.7  1738.9
#Mann= 10 ,-1 , 0
       0     .12       0    52.3     .08       0    74.1     .12       0
  124.26     .06       0  261.66     .12       0  296.35    .016       0
   356.3    .045       0   369.4    .016       0  412.09     .08       0
   442.5     .12       0
Bank Sta=356.3,369.4
XS Rating Curve= 0 ,0
Exp/Cntr=0.3,0.1

Type RM Length L Ch R = 1 ,8466.4  ,261.5,250,239.8
XS GIS Cut Line= 3
     2059337.102      207690.996     2058979.053       207762.44
     2058615.749      207870.375
#Sta/Elev= 30
       0 1690.62   65.661688.884   117.4 1688.17   156.5 1684.54     176 1681.25
   198.8 1675.74   224.9 1667.71  242.521660.278     251 1656.19   260.8 1654.25
   270.6  1648.8   296.6 1640.76   316.2 1638.47  351.161636.627   361.8 1636.28
   366.91636.615  370.081637.195  398.01 1638.49     437 1639.28   450.1  1645.7
  459.751646.664   469.7 1648.05   482.7 1655.32   541.5  1683.3   574.2 1695.36
   593.8 1699.78   629.8 1704.33   652.6 1704.82   688.6 1703.54   744.1 1699.09
#Mann= 8 ,-1 , 0
       0     .08       0   65.66     .06       0  242.52     .12       0
  351.16    .045       0   366.9     .12       0  370.08     .08       0
  398.01    .016       0  459.75     .12       0
#XS Ineff= 2 , 0
                          424.12         1640.38
Permanent Ineff=
       F       F
Bank Sta=351.16,366.9
XS Rating Curve= 0 ,0
Exp/Cntr=0.3,0.1

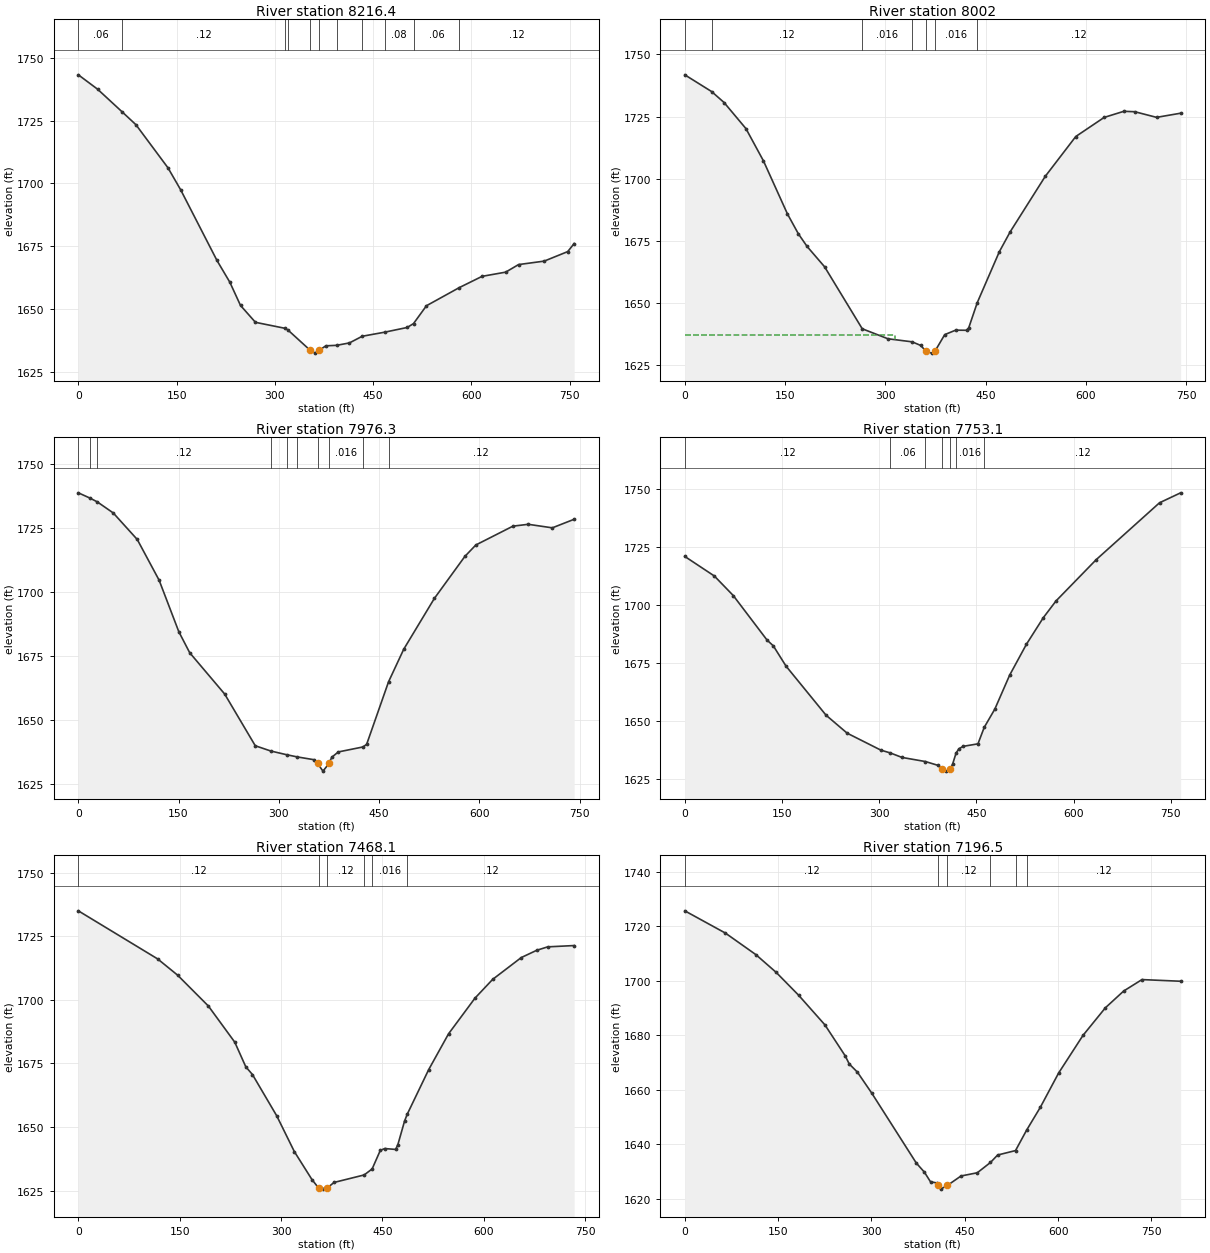
Type RM Length L Ch R = 1 ,8216.4  ,211.9,214.3,212.9
XS GIS Cut Line= 3
     2059151.906      207307.964     2058883.567      207550.087
     2058585.271      207809.405
#Sta/Elev= 30
       0 1743.22    29.3 1737.52   67.311728.371    87.9 1723.37   136.8 1706.21
   156.3  1697.4   211.6 1669.33   231.2 1660.69   247.5 1651.44   270.3 1644.72
  315.071642.355  319.581641.738   353.9 1633.58   361.4 1632.46     368 1633.69
   377.8 1635.37   394.1 1635.56   413.7 1636.52  433.241639.171  467.531640.796
   501.9 1642.67  511.53 1644.22   531.3 1651.32  581.511658.553   616.2 1663.02
   652.2 1664.69   671.8  1667.7     711 1669.08   746.9 1672.87   756.7 1676.09
#Mann= 11 ,-1 , 0
       0     .06       0   67.31     .12       0  315.07     .08       0
  319.58     .06       0   353.9    .045       0     368     .12       0
   394.1     .06       0  433.24    .016       0  467.53     .08       0
  511.53     .06       0  581.51     .12       0
Bank Sta=353.9,368
XS Rating Curve= 0 ,0
Exp/Cntr=0.3,0.1

Type RM Length L Ch R = 1 ,8002    ,25.7,25.7,26.3
XS GIS Cut Line= 2
     2059025.516       207189.98     2058451.489      207660.103
#Sta/Elev= 30
       0 1741.76   40.221735.018    58.8 1730.62    91.5 1720.14   117.7 1707.17
   153.6 1685.84     170 1677.82     183 1672.76   209.2 1664.58  265.551639.658
     304 1635.64  340.291634.407     353 1632.96  360.961630.638   369.4 1629.87
  374.341630.634     389 1637.31   405.3  1639.1   421.6 1639.06   424.9 1640.05
  437.691650.177   470.7 1670.64     487 1678.67   539.3  1700.9   585.1 1716.96
   627.6 1724.64     657 1727.09   673.3 1726.93     706 1724.66     742 1726.33
#Mann= 7 ,-1 , 0
       0     .06       0   40.22     .12       0  265.55    .016       0
  340.29     .06       0  360.96    .045       0  374.34    .016       0
  437.69     .12       0
#XS Ineff= 2 , 0
          314.96 1637.28
Permanent Ineff=
       F       F
Bank Sta=360.96,374.34
XS Rating Curve= 0 ,0
Exp/Cntr=0.3,0.1

Type RM Length L Ch R = 1 ,7976.3  ,214.9,223.2,230.2
XS GIS Cut Line= 2
     2059011.324      207168.366     2058437.297      207638.488
#Sta/Elev= 30
       0 1738.75   17.42 1736.69   28.371735.211    52.3 1730.87    88.2  1720.5
   120.9 1704.58   150.4 1684.42   166.7 1676.21     219 1660.07   264.8 1639.84
  287.951637.793  311.541636.348  327.781635.469     353 1634.37  357.96 1632.92
   366.1 1629.92   375.2 1632.92   379.2 1635.32     389 1637.42  426.09 1639.38
   431.5 1640.43  464.271664.875     487 1677.61   532.8 1697.46   578.5  1713.9
   594.9 1718.36   650.4 1725.72   673.3 1726.44   709.3 1725.06     742 1728.41
#Mann= 10 ,-1 , 0
       0     .12       0   17.42     .06       0   28.37     .12       0
  287.95    .016       0  311.54     .08       0  327.78    .016       0
  357.96    .045       0   375.2    .016       0  426.09     .08       0
  464.27     .12       0
Bank Sta=357.96,375.2
XS Rating Curve= 0 ,0
Exp/Cntr=0.3,0.1

Type RM Length L Ch R = 1 ,7753.1  ,290.9,284.9,278.1
XS GIS Cut Line= 3
     2058955.087        207118.2     2058587.416      207239.897
     2058233.352      207372.373
#Sta/Elev= 30
       0 1720.75    45.6 1712.33    74.8 1703.92   126.9 1684.77   136.7 1682.23
   156.2 1673.55     218 1652.41   250.6 1644.66   302.7 1637.35  317.111636.162
   335.2 1634.22  371.441632.442   390.6 1630.82   397.1 1629.33   403.6 1628.32
   410.1 1629.31   413.4 1631.37  418.731636.102   423.1 1637.95   429.6 1638.99
   452.5 1640.07  462.24 1647.21   478.5 1655.01   501.4 1669.64   527.4 1682.99
   553.5 1694.44     573  1701.6     635 1719.37   732.7 1743.85   765.3 1748.14
#Mann= 7 ,-1 , 0
       0     .12       0  317.11     .06       0  371.44     .12       0
   397.1    .045       0   410.1     .12       0  418.73    .016       0
  462.24     .12       0
Bank Sta=397.1,410.1
XS Rating Curve= 0 ,0
Exp/Cntr=0.3,0.1

Type RM Length L Ch R = 1 ,7468.1  ,277.6,271.7,261.8
XS GIS Cut Line= 3
     2058749.585      206809.093     2058473.841      207048.791
     2058166.488      207252.095
#Sta/Elev= 30
       0 1734.96   117.4 1716.06   146.8 1709.71   192.5 1697.54   231.6 1683.32
   247.9 1673.64   257.7 1670.63   293.6 1654.42   319.7 1640.35   345.8 1629.34
   355.6 1626.04   362.1 1625.58   368.6 1626.07   378.4  1628.2  423.111631.155
  434.891633.519   446.9 1640.77   453.4 1641.53   469.7 1641.18     473  1643.1
   482.8 1652.26  486.661654.926   518.6 1672.56     548 1686.63   587.1 1700.64
   613.2    1708   655.6 1716.59   678.4 1719.44   694.7  1720.8   733.9 1721.31
#Mann= 6 ,-1 , 0
       0     .12       0   355.6    .045       0   368.6     .12       0
  423.11     .06       0  434.89    .016       0  486.66     .12       0
Bank Sta=355.6,368.6
XS Rating Curve= 0 ,0
Exp/Cntr=0.3,0.1

Type RM Length L Ch R = 1 ,7196.5  ,236.9,248.2,258.6
XS GIS Cut Line= 3
     2058663.879       206733.24     2058309.712      206823.518
     2058073.601      207184.629
#Sta/Elev= 30
       0 1725.62    65.3 1717.45   114.2 1709.56   146.8 1703.06   182.8  1694.7
   225.2 1683.79   257.8 1672.43   264.3 1669.45   277.4 1666.46   300.2 1658.85
     372 1633.13   385.1 1629.76   394.9 1626.23   404.7 1625.83   407.1 1624.91
   411.2 1623.54   422.1  1624.9   443.9 1628.36   470.1 1629.54  491.241633.316
   502.8 1636.05  531.53 1637.68  549.371645.174   571.4 1653.55   600.8 1666.12
     640 1679.94     676 1690.06   705.4 1696.21   734.8  1700.4   796.9 1699.79
#Mann= 6 ,-1 , 0
       0     .12       0   407.1    .045       0   422.1     .12       0
  491.24    .016       0  531.53     .08       0  549.37     .12       0
Bank Sta=407.1,422.1
XS Rating Curve= 0 ,0
Exp/Cntr=0.3,0.1

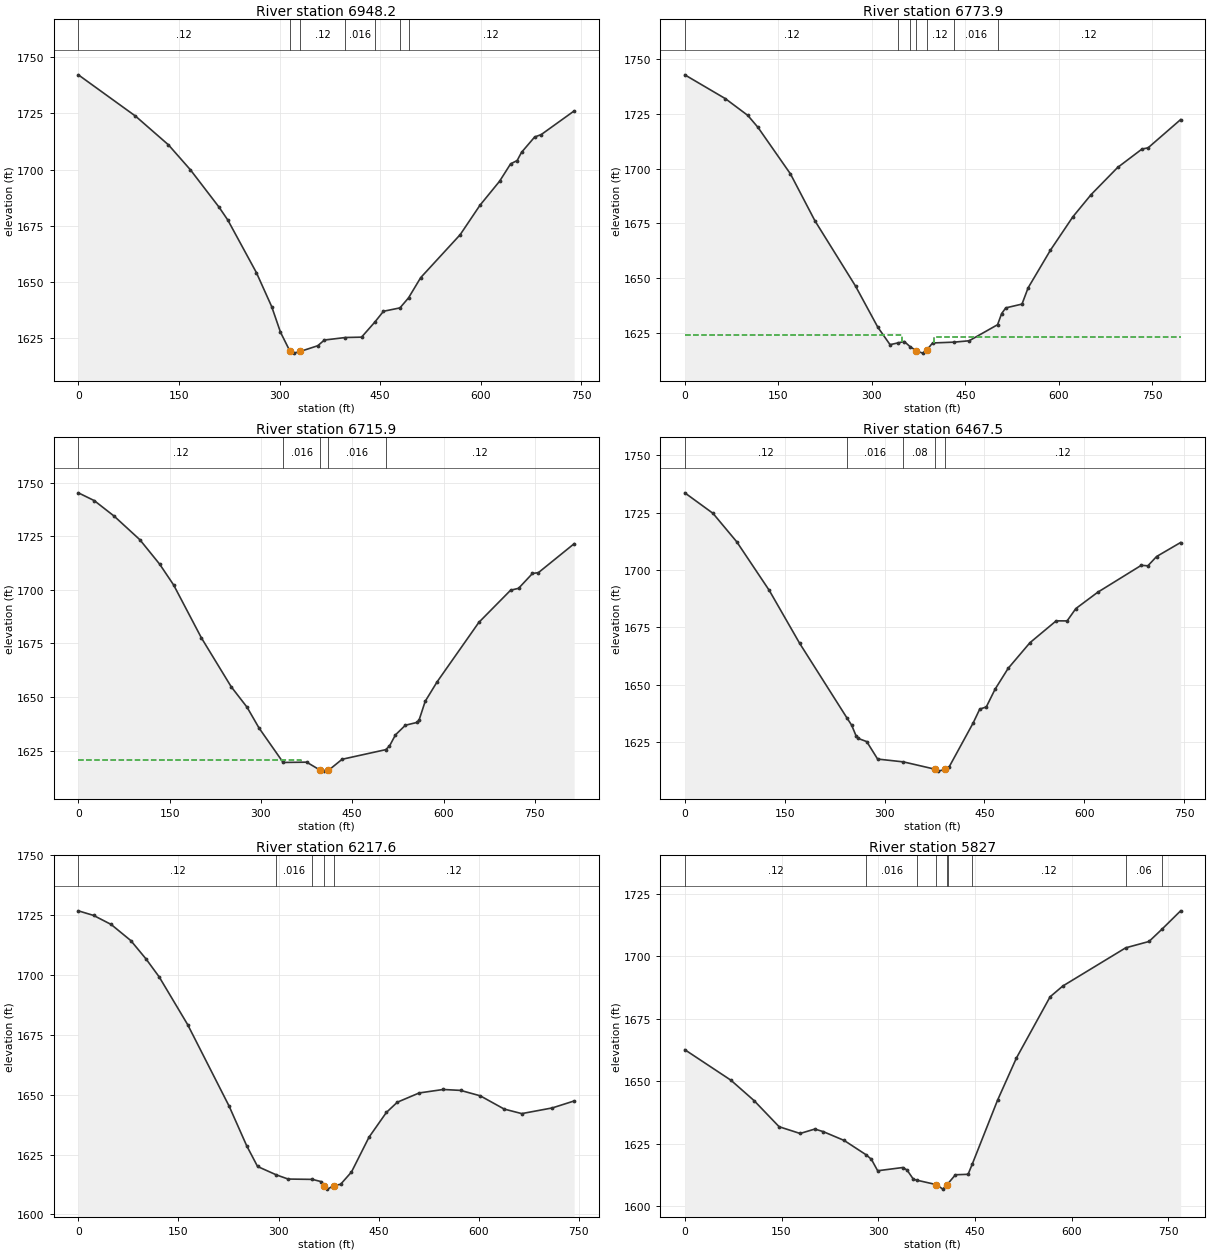
Type RM Length L Ch R = 1 ,6948.2  ,206.3,174.3,140.7
XS GIS Cut Line= 3
     2058434.712      206394.698     2058273.254      206601.296
     2057854.851      206830.462
#Sta/Elev= 30
       0  1742.2    85.2 1723.84   134.4 1711.03   167.2  1699.9   209.8 1683.31
   222.9 1677.56   265.5 1654.18   288.3 1639.05   301.4 1627.67   315.71619.093
     321 1618.34   330.8 1619.08     357 1621.63   366.8 1624.15  398.091625.291
   422.3 1625.45  442.091632.157     455 1636.97  479.551638.471  492.361642.944
   510.5 1651.95   569.4 1671.08   598.8 1684.13   628.2 1694.88   644.5 1702.57
   654.3 1704.05   660.8  1707.7   680.4 1714.53   690.2 1715.61   739.3 1726.13
#Mann= 7 ,-1 , 0
       0     .12       0   315.7    .045       0   330.8     .12       0
  398.09    .016       0  442.09     .12       0  479.55    .016       0
  492.36     .12       0
Bank Sta=315.7,330.8
XS Rating Curve= 0 ,0
Exp/Cntr=0.3,0.1

Type RM Length L Ch R = 1 ,6773.9  ,39,58,55.2
XS GIS Cut Line= 4
     2058423.651      206390.301      2058093.79      206493.383
     2058122.154      206569.539      2057817.25      206776.788
#Sta/Elev= 30
       0 1742.93    65.2 1732.01   101.1 1724.36   117.4 1718.89   169.5  1697.6
   208.7 1676.19   273.9 1646.28   309.7 1627.45   329.3 1619.47   342.71620.317
   352.1 1620.92  361.261618.597   371.4 1616.72   381.4  1615.6   387.8 1616.87
   397.6 1620.25  431.76 1620.62   456.2 1621.25  501.821628.603   508.4 1633.73
     515  1636.3     541 1638.04   550.8 1645.46   586.7 1662.74   622.6 1677.97
     652 1688.17   694.4 1700.54   733.5 1708.97   743.3 1709.53   795.5 1722.46
#Mann= 7 ,-1 , 0
       0     .12       0   342.7    .016       0  361.26     .12       0
   371.4    .045       0   387.8     .12       0  431.76    .016       0
  501.82     .12       0
#XS Ineff= 2 , 0
           348.3 1623.86  399.83         1622.89
Permanent Ineff=
       F       F
Bank Sta=371.4,387.8
XS Rating Curve= 0 ,0
Exp/Cntr=0.3,0.1

Type RM Length L Ch R = 1 ,6715.9  ,230.8,248.4,274.2
XS GIS Cut Line= 4
     2058414.168      206372.577      2058044.16      206489.765
     2058076.929      206577.525     2057801.321      206764.157
#Sta/Elev= 30
       0 1745.24    26.1 1741.62    58.7 1734.41   101.1 1723.37   133.7 1711.94
   156.6 1702.26   202.2  1677.6   251.1 1654.83   277.2 1645.26   296.8  1635.6
  336.511619.506   375.1 1619.64   397.8 1615.83   404.3 1615.46   410.7 1615.77
   433.4 1620.99  504.921625.465   511.2 1627.16     521 1632.36   537.3 1636.86
   556.9 1638.21   560.1 1639.52   569.9 1648.04   589.5 1657.12     658 1684.82
   710.2 1699.83   723.3 1700.71   746.1 1707.63   755.9 1708.03   814.6 1721.51
#Mann= 5 ,-1 , 0
       0     .12       0  336.51    .016       0   397.8    .045       0
   410.7    .016       0  504.92     .12       0
#XS Ineff= 2 , 0
           366.4 1620.63
Permanent Ineff=
       F       F
Bank Sta=397.8,410.7
XS Rating Curve= 0 ,0
Exp/Cntr=0.3,0.1

Type RM Length L Ch R = 1 ,6467.5  ,241,249.9,266.8
XS GIS Cut Line= 3
     2058231.788      206127.062     2057899.274      206319.074
     2057672.403      206599.547
#Sta/Elev= 30
       0 1733.68    42.3 1724.74    78.1 1712.28   126.9 1691.08   172.5    1668
  243.541635.427   250.6 1632.28   257.1 1627.71   260.3 1626.52   273.3 1625.09
   289.6 1617.49  328.431616.248   376.5 1613.01   380.7 1612.22   391.5 1613.02
   397.1  1614.1   433.2  1633.3     443  1639.3   452.8 1640.22     466 1647.96
   485.6 1657.05   518.4 1668.27   557.8 1677.81   574.2 1677.78   587.3 1683.16
   620.1 1690.27   685.7 1702.06   695.5 1701.82   708.6 1705.88   744.7    1712
#Mann= 5 ,-1 , 0
       0     .12       0  243.54    .016       0  328.43     .08       0
   376.5    .045       0   391.5     .12       0
Bank Sta=376.5,391.5
XS Rating Curve= 0 ,0
Exp/Cntr=0.3,0.1

Type RM Length L Ch R = 1 ,6217.6  ,388,390.6,390.6
XS GIS Cut Line= 3
     2058211.285      206059.398     2057832.609       206088.36
      2057474.43      206147.155
#Sta/Elev= 30
       0 1726.76    22.9 1724.83    49.1 1721.08    78.6 1714.34   101.5 1706.64
   121.1 1699.18   163.7 1679.28   225.9 1645.19   252.1 1628.72   268.5    1620
  296.821616.471   314.3 1614.75  350.741614.607   363.4  1613.7  368.761611.966
   373.2 1610.54     383 1612.03   392.9 1612.55   409.2 1617.69   435.4  1632.2
   461.5 1642.57   477.9 1646.84   510.6  1650.7   546.6 1652.15   572.7 1651.77
   602.1 1649.51   638.1 1643.96   664.3 1642.08     710 1644.45   742.8 1647.36
#Mann= 5 ,-1 , 0
       0     .12       0  296.82    .016       0  350.74     .12       0
  368.76    .045       0     383     .12       0
Bank Sta=368.76,383
XS Rating Curve= 0 ,0
Exp/Cntr=0.3,0.1

Type RM Length L Ch R = 1 ,5827    ,71.3,70.1,69.2
XS GIS Cut Line= 3
     2058156.877      205865.329     2057847.632       205728.61
     2057421.199      205789.374
#Sta/Elev= 30
       0 1662.61    71.5  1650.4   107.3 1642.27   146.3 1631.78   178.8 1629.09
   201.6 1630.85   214.6 1629.84   247.1  1626.3  281.48 1620.51   289.4 1618.73
   299.1 1614.17   338.1 1615.47   344.6 1614.47   354.4 1610.81  360.33 1610.37
   390.3 1608.61   400.1 1606.82   406.6 1608.52  408.151609.035   419.7 1612.57
   439.3 1612.75  446.111617.038     485  1642.4   514.3  1659.3   566.5 1683.77
   586.1 1688.07  683.711703.367   719.9 1705.91  739.931710.813   768.9 1718.17
#Mann= 9 ,-1 , 0
       0     .12       0  281.48    .016       0  360.33     .12       0
   390.3    .045       0   406.6     .12       0  408.15    .016       0
  446.11     .12       0  683.71     .06       0  739.93     .12       0
Bank Sta=390.3,406.6
XS Rating Curve= 0 ,0
Exp/Cntr=0.3,0.1