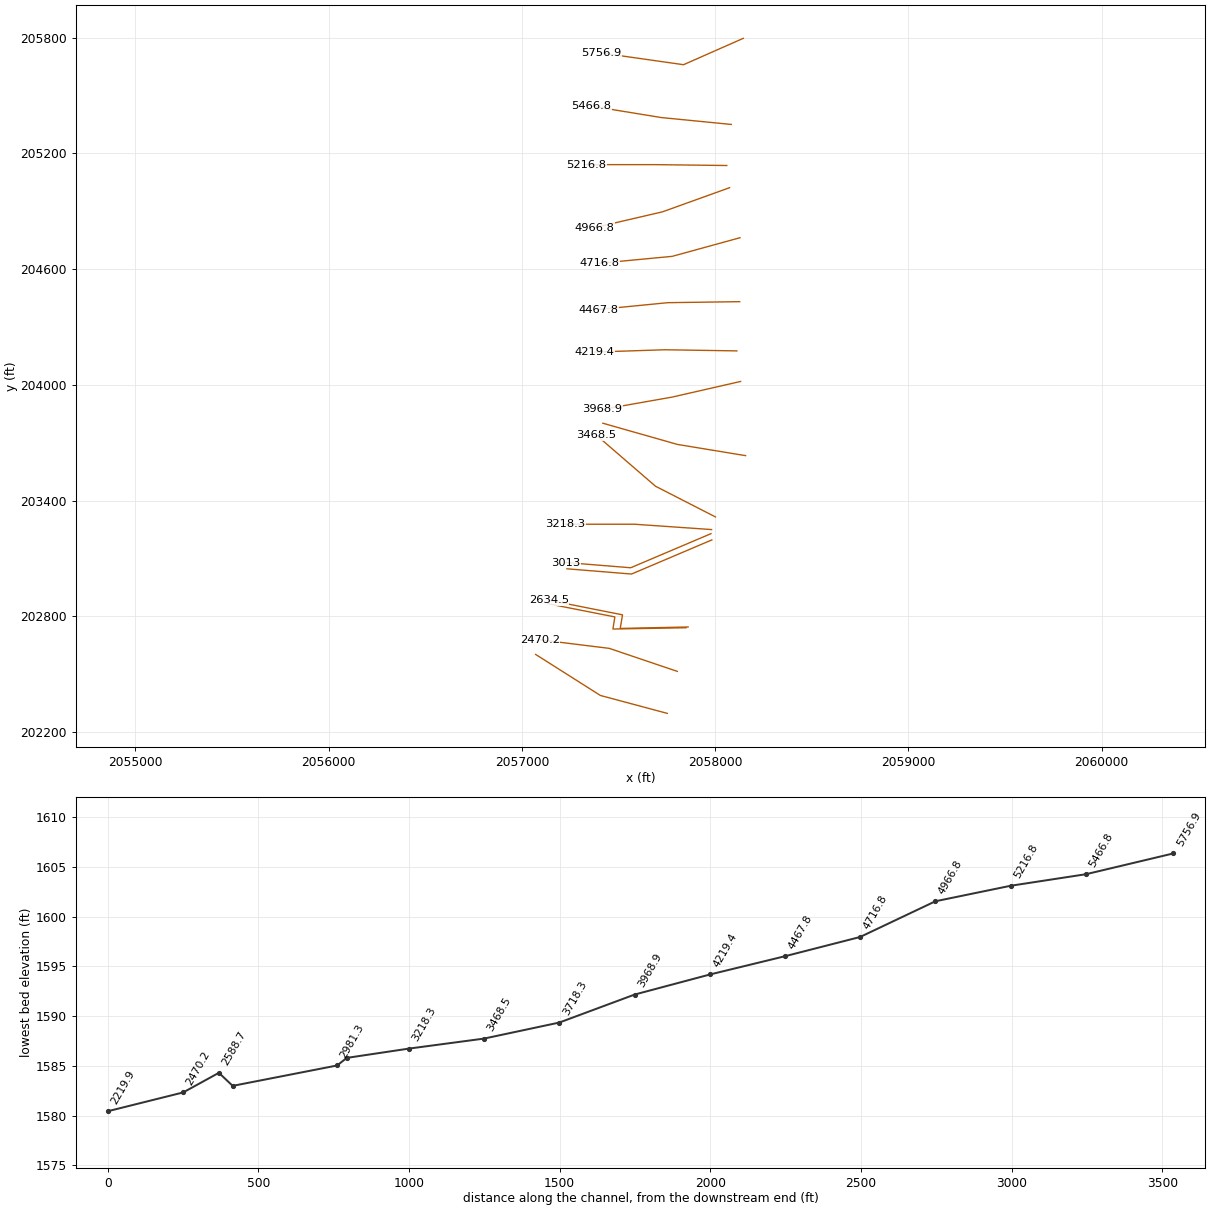
HEC-RAS study INDIANDFT.prj: INDIANDFT

--- INDIANDFT.g01 (geometry) --- (continued)

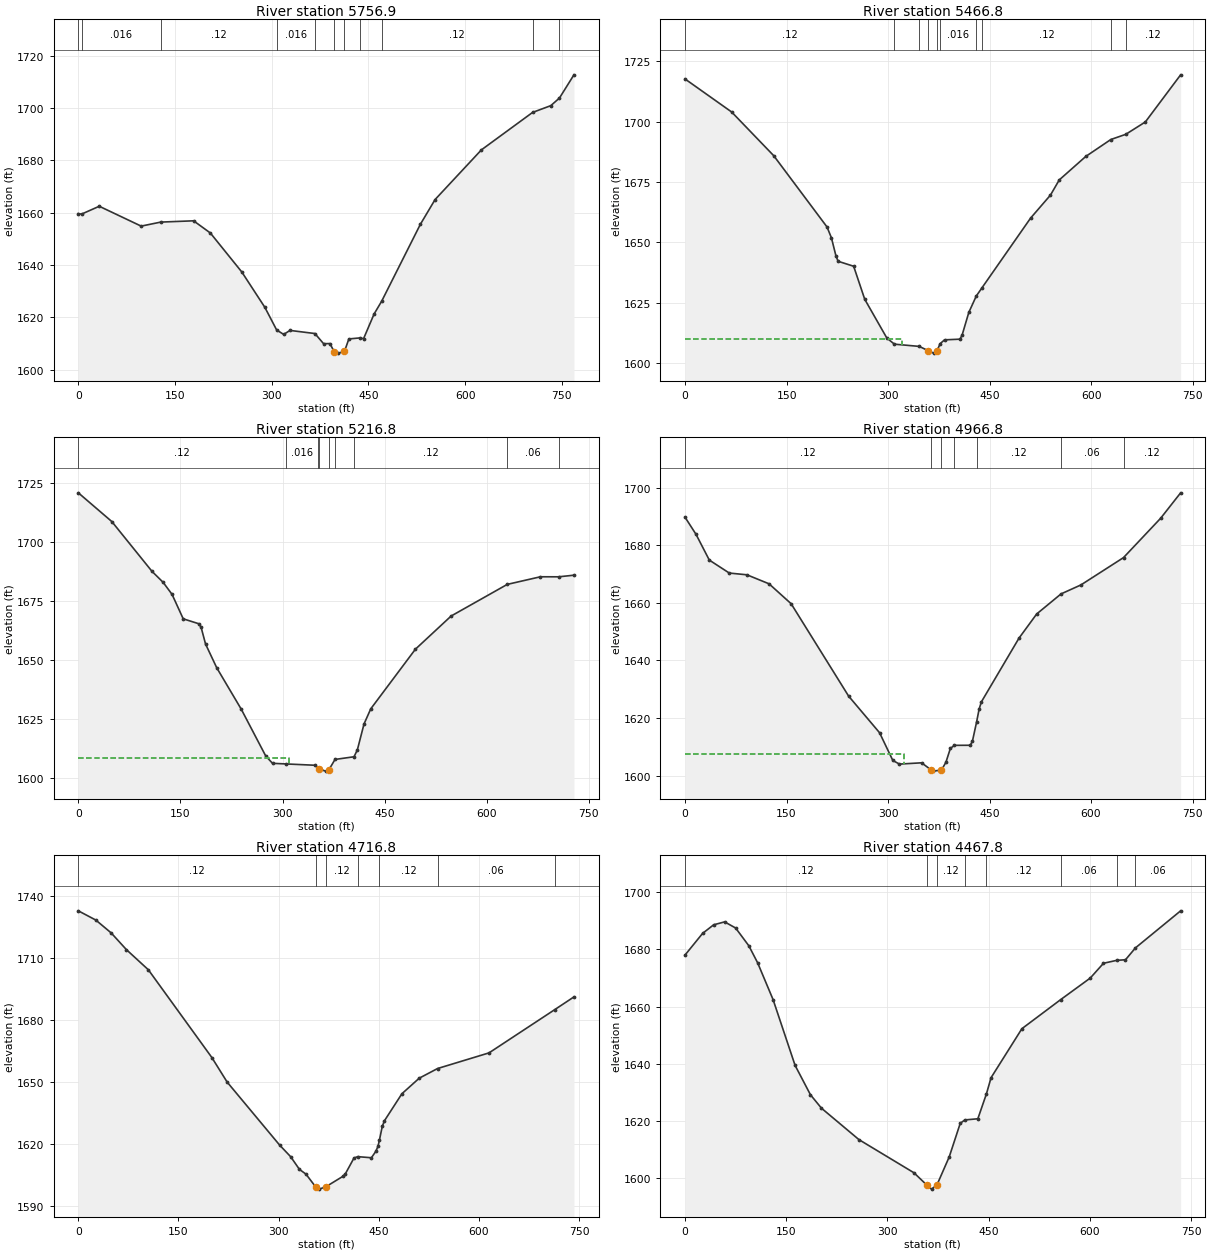
Type RM Length L Ch R = 1 ,5756.9  ,288.5,290.1,289
XS GIS Cut Line= 3
     2058146.026       205796.97     2057836.781      205660.251
     2057410.349      205721.015
#Sta/Elev= 30
       0 1659.66     5.1  1659.5    32.5 1662.49    97.5  1654.9  127.911656.438
   178.8 1656.93   204.8 1652.28   253.6 1637.38   289.4 1623.86  307.691615.205
   318.6 1613.51   328.4 1615.04  367.031613.849   380.5 1609.97   390.3 1610.01
   396.9 1606.95   403.4 1606.36   412.9    1607   419.7 1611.78   437.61612.193
   442.5 1611.86   458.9 1621.34  470.541626.165   530.6 1655.57   553.5 1665.06
   625.3 1684.03  704.781698.359     733 1700.94  746.451703.855   768.9 1712.72
#Mann= 11 ,-1 , 0
       0     .12       0     5.1    .016       0  127.91     .12       0
  307.69    .016       0  367.03     .12       0   396.9    .045       0
   412.9     .12       0   437.6    .016       0  470.54     .12       0
  704.78     .06       0  746.45     .12       0
Bank Sta=396.9,412.9
XS Rating Curve= 0 ,0
Exp/Cntr=0.3,0.1

Type RM Length L Ch R = 1 ,5466.8  ,247.7,250,253.3
XS GIS Cut Line= 3
     2058083.778      205350.532     2057721.905      205386.174
     2057358.549      205445.698
#Sta/Elev= 30
       0 1717.59    68.8 1703.95     131 1685.87   209.7  1656.4   216.2 1651.91
   222.8 1644.52     226 1642.24     249 1640.18   265.4  1626.5   298.1 1610.46
  309.271607.971  345.791607.053  358.63 1605.35   366.9 1604.27  372.331605.323
  376.571608.142   383.2 1609.76     406 1610.04   409.2 1611.78     419 1621.07
  430.091627.893  438.591631.316   510.2 1660.06   539.6 1669.59   552.6 1675.87
   591.7 1685.56  628.751692.567  650.771694.705   679.7 1699.82   731.8  1719.3
#Mann= 10 ,-1 , 0
       0     .12       0  309.27    .016       0  345.79     .12       0
  358.63    .045       0  372.33     .12       0  376.57    .016       0
  430.09     .06       0  438.59     .12       0  628.75     .06       0
  650.77     .12       0
#XS Ineff= 2 , 0
          320.44 1609.91
Permanent Ineff=
       F       F
Bank Sta=358.63,372.33
XS Rating Curve= 0 ,0
Exp/Cntr=0.3,0.1

Type RM Length L Ch R = 1 ,5216.8  ,241.1,250,254.6
XS GIS Cut Line= 3
     2058060.675      205137.528     2057696.731      205141.966
      2057332.64      205142.094
#Sta/Elev= 30
       0 1721.03    49.2 1708.86   108.2 1687.77   124.6  1683.1   137.7    1678
   154.1 1667.64   177.1 1665.55   180.4 1664.04   186.9 1656.98   203.3 1646.92
   239.4 1629.33   275.4 1609.48   285.3 1606.42  305.031606.158   347.6  1605.6
   352.71604.268   354.1 1603.81     364 1603.11  368.241603.734  377.091608.064
  405.021609.196   409.9 1612.08   419.7 1623.08   429.6  1629.5   495.2 1654.77
   547.7 1668.83  630.151682.235   678.9 1685.46  705.721685.446   728.1 1686.13
#Mann= 9 ,-1 , 0
       0     .12       0  305.03    .016       0   352.7     .12       0
   354.1    .045       0  368.24     .12       0  377.09    .016       0
  405.02     .12       0  630.15     .06       0  705.72     .12       0
#XS Ineff= 2 , 0
           309.6 1608.77
Permanent Ineff=
       F       F
Bank Sta=354.1,368.24
XS Rating Curve= 0 ,0
Exp/Cntr=0.3,0.1

Type RM Length L Ch R = 1 ,4966.8  ,251.1,250,245.8
XS GIS Cut Line= 3
     2058075.032      205022.485     2057727.708      204897.247
     2057374.028       204814.88
#Sta/Elev= 30
       0 1689.74    16.3 1683.77    35.9 1674.84    65.4 1670.34    91.5 1669.73
   124.2  1666.6   156.8 1659.69   241.8 1627.59   287.5 1614.88   307.1 1605.25
   316.9 1603.99   349.6 1604.44  364.021601.916     366 1601.55     379 1601.91
   385.6 1604.66   392.1 1609.42  398.061610.507   421.6 1610.53   424.8 1612.03
   430.81618.525   434.6 1623.06   437.9 1625.58   493.5 1647.72   519.7 1656.13
   555.7  1663.1   585.1 1666.22  647.991675.704   702.9 1689.38   732.4  1698.2
#Mann= 7 ,-1 , 0
       0     .12       0  364.02    .045       0     379     .12       0
  398.06    .016       0   430.8     .12       0   555.7     .06       0
  647.99     .12       0
#XS Ineff= 2 , 0
          323.63 1607.43
Permanent Ineff=
       F       F
Bank Sta=364.02,379
XS Rating Curve= 0 ,0
Exp/Cntr=0.3,0.1

Type RM Length L Ch R = 1 ,4716.8  ,253.6,248.9,248
XS GIS Cut Line= 3
     2058129.124      204763.082     2057778.299      204666.539
     2057401.633      204630.593
#Sta/Elev= 30
       0 1733.03    26.2 1728.55    49.2 1722.31    72.1 1714.17   104.9 1704.41
     200 1661.81   222.9  1649.9   301.6 1619.28     318 1613.69   331.1 1607.55
   340.9 1605.24  355.341599.084   360.6 1597.96   370.4 1599.04   396.5 1604.22
   399.8 1605.33   412.8 1613.05  418.431613.719   438.9 1613.19   445.4 1616.24
   448.7 1618.65  450.921621.758   455.2 1628.45   458.5 1631.18   484.6 1644.26
   510.6 1651.82  538.051656.502     615 1664.08  713.611685.111   742.2 1691.25
#Mann= 7 ,-1 , 0
       0     .12       0  355.34    .045       0   370.4     .12       0
  418.43    .016       0  450.92     .12       0  538.05     .06       0
  713.61     .12       0
Bank Sta=355.34,370.4
XS Rating Curve= 0 ,0
Exp/Cntr=0.3,0.1

Type RM Length L Ch R = 1 ,4467.8  ,248.8,248.4,247.2
XS GIS Cut Line= 3
     2058127.316      204431.507     2057755.469      204426.281
      2057394.74      204390.752
#Sta/Elev= 30
       0 1678.04    26.1 1685.64    42.4 1688.63    58.7 1689.66      75 1687.51
    94.6 1681.27   107.6 1675.32   130.5 1662.42   163.1 1639.38   185.9 1629.08
   202.2 1624.38   257.7 1613.38   339.3 1601.75   358.21597.476   365.4 1596.03
  373.311597.497   391.5 1607.33   407.8 1619.07  414.551620.269   433.9 1620.68
   446.71629.454   453.5 1635.08   499.2 1652.24  556.421662.383   600.5 1669.98
   620.1 1675.16  639.661676.179   652.7 1676.39  667.481680.556   734.4 1693.53
#Mann= 8 ,-1 , 0
       0     .12       0   358.2    .045       0  373.31     .12       0
  414.55    .016       0   446.7     .12       0  556.42     .06       0
  639.66    .016       0  667.48     .06       0
Bank Sta=358.2,373.31
XS Rating Curve= 0 ,0
Exp/Cntr=0.3,0.1

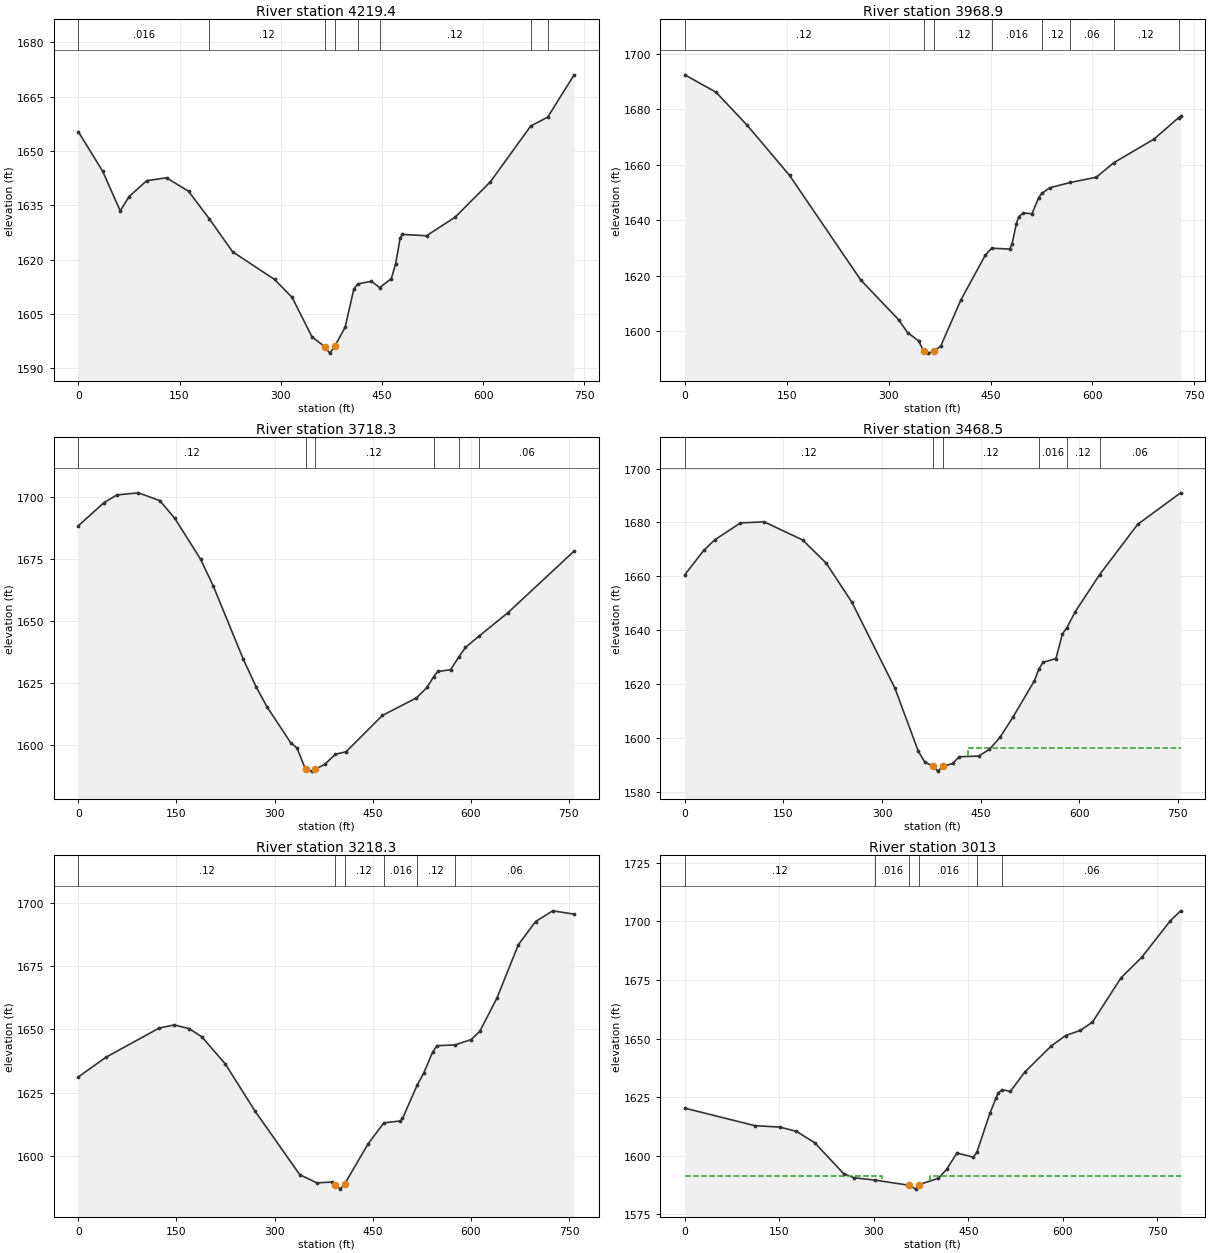
Type RM Length L Ch R = 1 ,4219.4  ,244.4,250.5,253.2
XS GIS Cut Line= 3
     2058112.554      204176.257     2057740.134      204182.119
     2057377.913      204170.261
#Sta/Elev= 30
       0 1655.29    35.9 1644.43    62.1 1633.46    75.2  1637.4   101.3 1641.77
   130.7 1642.58   163.4 1638.85  194.081631.262   228.7 1622.16   290.8 1614.53
   316.9 1609.57   346.3  1598.7     365 1596.01   372.5  1594.2     380 1596.07
   395.3 1601.29   408.4 1611.89  413.991613.289   434.5 1614.02  446.621612.287
   463.9 1614.76   470.4 1618.89     477 1625.96   480.2 1626.96   516.1 1626.58
   558.6 1631.73   610.8 1641.48  670.571656.875  695.631659.306   734.9 1670.98
#Mann= 8 ,-1 , 0
       0    .016       0  194.08     .12       0     365    .045       0
     380     .12       0  413.99    .016       0  446.62     .12       0
  670.57    .016       0  695.63     .06       0
Bank Sta=365,380
XS Rating Curve= 0 ,0
Exp/Cntr=0.3,0.1

Type RM Length L Ch R = 1 ,3968.9  ,258.9,250.7,239.5
XS GIS Cut Line= 3
     2058132.176      204017.798     2057777.498      203936.621
     2057417.207      203872.878
#Sta/Elev= 30
       0 1692.34    45.9 1686.09    91.8 1674.19   154.1 1656.17     259 1618.49
   314.7  1604.2   327.8 1599.59   344.2  1596.6   351.61592.794   357.3 1592.18
   367.1 1592.78   376.9 1594.86   406.3 1611.33   442.2 1627.42  451.521629.944
   478.2 1629.63   481.5  1631.4     488 1638.81   491.3  1641.2   497.8 1642.63
   510.9 1642.33   520.7 1648.13  525.361649.637     537  1651.7  567.421653.595
   605.6 1655.49  631.091660.668   690.5 1669.21   726.61676.897   729.7 1677.41
#Mann= 8 ,-1 , 0
       0     .12       0   351.6    .045       0   367.1     .12       0
  451.52    .016       0  525.36     .12       0  567.42     .06       0
  631.09     .12       0   726.6     .06       0
Bank Sta=351.6,367.1
XS Rating Curve= 0 ,0
Exp/Cntr=0.3,0.1

Type RM Length L Ch R = 1 ,3718.3  ,261.5,249.7,238.9
XS GIS Cut Line= 3
     2058157.569      203633.113     2057804.991      203691.324
     2057419.482       203801.13
#Sta/Elev= 30
       0 1688.51    39.3 1697.89      59 1700.97    91.8 1701.82   124.6 1698.68
   147.5  1691.5   186.9 1675.02   206.5 1664.08   252.4 1634.49   272.1  1623.3
   288.5 1615.36   324.6  1600.9   334.4  1598.7   347.5 1590.05   357.4 1589.36
   361.9 1590.04   376.9 1592.14   393.2 1596.19   409.5 1597.21   464.9 1611.86
     517 1618.93   533.3 1623.23  543.241627.511   549.6 1629.62   569.2 1630.33
  582.011635.565     592 1639.37  612.731643.925   657.2 1653.45   758.2  1678.3
#Mann= 6 ,-1 , 0
       0     .12       0   347.5    .045       0   361.9     .12       0
  543.24    .016       0  582.01     .08       0  612.73     .06       0
Bank Sta=347.5,361.9
XS Rating Curve= 0 ,0
Exp/Cntr=0.3,0.1

Type RM Length L Ch R = 1 ,3468.5  ,234.8,250.3,265.2
XS GIS Cut Line= 3
     2058001.849      203315.303     2057691.657       203474.56
     2057385.176      203739.903
#Sta/Elev= 30
       0 1660.61    29.3 1669.77    45.6 1673.56    84.7 1679.82   120.6 1680.24
   179.2 1673.51   215.1  1664.9   254.2 1650.37   319.4 1618.61   355.2 1595.11
     365 1591.11   378.1 1589.52   384.6 1587.75  392.931589.513   407.5  1590.6
   417.3 1593.09   446.8 1593.34   463.1 1595.78   479.5 1600.32   499.1 1607.78
   531.8  1621.3   538.41625.577   544.8 1628.09   564.5 1629.51   574.3 1638.65
  581.021640.918   593.9 1646.92  630.74 1660.59   688.7 1679.29   754.1 1690.99
#Mann= 6 ,-1 , 0
       0     .12       0   378.1    .045       0  392.93     .12       0
   538.4    .016       0  581.02     .12       0  630.74     .06       0
#XS Ineff= 2 , 0
                           431.3         1596.44
Permanent Ineff=
       F       F
Bank Sta=378.1,392.93
XS Rating Curve= 0 ,0
Exp/Cntr=0.3,0.1

Type RM Length L Ch R = 1 ,3218.3  ,194,205.3,213.7
XS GIS Cut Line= 3
     2057981.827      203249.808     2057582.457      203277.497
     2057224.868      203277.497
#Sta/Elev= 30
       0  1631.2    42.3 1639.01   123.7 1650.59   146.5  1651.8   169.2 1650.36
   188.8  1647.1   224.6 1636.37   270.1 1617.67   338.5 1592.47   364.5 1589.23
   387.3 1589.54   392.8 1588.51   400.3 1586.74   406.9 1588.71     443 1604.71
  467.081613.017   492.2 1613.76   495.5 1614.73  518.061628.005   528.3 1632.92
   541.4 1640.93     548 1643.58  575.621643.879   600.4 1646.01   613.6 1649.26
   639.8 1662.43   672.6  1683.6   698.9 1692.76   725.1 1697.02   757.9 1695.72
#Mann= 6 ,-1 , 0
       0     .12       0   392.8    .045       0   406.9     .12       0
  467.08    .016       0  518.06     .12       0  575.62     .06       0
Bank Sta=392.8,406.9
XS Rating Curve= 0 ,0
Exp/Cntr=0.3,0.1

Type RM Length L Ch R = 1 ,3013    ,31.7,31.7,31.7
XS GIS Cut Line= 3
     2057978.925       203228.61     2057563.344      203051.744
     2057229.142      203078.871
#Sta/Elev= 30
       0 1620.33   111.3 1612.86   150.6 1612.27   176.7  1610.5   206.2  1605.6
     252 1592.44   268.4 1590.66  302.271589.643   356.2 1587.44   366.6 1585.81
   371.2 1587.69   402.6 1590.44   415.6 1594.27     432 1601.19   458.2 1599.44
  463.621601.589   484.2 1618.07     494 1624.64   497.2 1626.73  503.821628.172
   516.8 1627.51   539.6 1635.71   581.9 1646.92   604.6  1651.3   627.4 1653.44
     647 1656.99   692.6 1675.97   725.1 1684.58   770.7 1700.23     787 1704.45
#Mann= 6 ,-1 , 0
       0     .12       0  302.27    .016       0   356.2    .045       0
   371.2    .016       0  463.62     .08       0  503.82     .06       0
#XS Ineff= 2 , 0
          313.56 1591.35  389.91         1591.26
Permanent Ineff=
       F       F
Bank Sta=356.2,371.2
XS Rating Curve= 0 ,0
Exp/Cntr=0.3,0.1

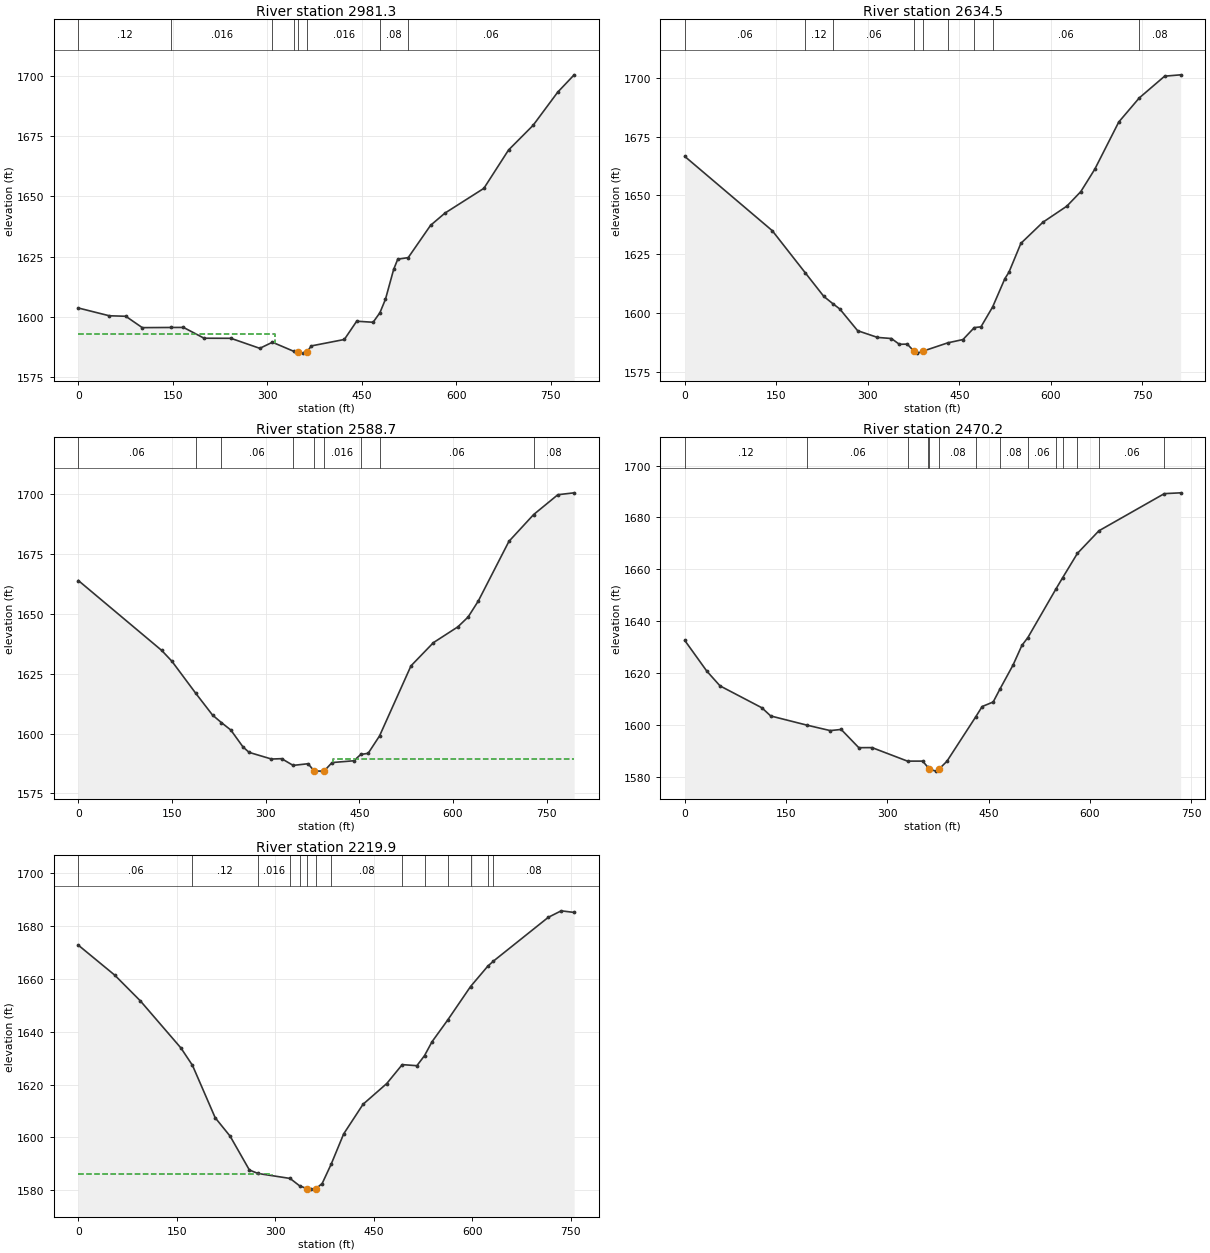
Type RM Length L Ch R = 1 ,2981.3  ,397.3,346.8,296
XS GIS Cut Line= 3
     2057983.265      203196.058     2057567.684      203019.192
     2057233.482      203046.319
#Sta/Elev= 30
       0 1603.75    49.1 1600.53    75.3 1600.32   101.5 1595.61  146.84 1595.68
   166.9  1595.7   199.6 1591.23   242.2 1591.19     288 1587.04   308.1 1589.56
  342.441585.744   348.5 1585.61   356.7 1585.05   363.3 1585.71   369.8 1588.04
   422.2  1590.7   441.8 1598.27   467.9 1597.84  478.691601.796   487.5 1607.38
   500.5 1619.74     507 1623.97  523.611624.621   559.1    1638   581.9 1643.06
   643.7 1653.32   682.8 1669.19   721.8 1679.42   760.9 1693.17     787 1700.35
#Mann= 8 ,-1 , 0
       0     .12       0  146.84    .016       0   308.1     .12       0
  342.44    .016       0   348.5    .045       0   363.3    .016       0
  478.69     .08       0  523.61     .06       0
#XS Ineff= 2 , 0
           312.9 1592.77
Permanent Ineff=
       F       F
Bank Sta=348.5,363.3
XS Rating Curve= 0 ,0
Exp/Cntr=0.3,0.1

Type RM Length L Ch R = 1 ,2634.5  ,13.9,45.8,45.7
XS GIS Cut Line= 4
     2057860.653      202744.669      2057509.09      202737.074
     2057521.026      202807.603     2057139.081      202883.558
#Sta/Elev= 30
       0  1666.6   143.3 1635.06  197.67 1617.06   227.9 1607.09  242.961603.947
     254 1601.77   283.3 1592.53   315.8 1589.68   338.6 1589.21   351.6 1586.76
   364.6 1586.83  375.551583.837   380.9    1583   389.71583.779   431.11587.381
   455.9 1588.77  474.371593.842   485.4 1594.18  504.491602.623   524.6 1614.68
   531.2 1617.36   550.8 1629.65   586.8 1638.61   626.1 1645.46     649 1651.64
   671.9 1661.16   711.2 1681.22  744.851691.473   786.4 1700.71   812.6 1701.28
#Mann= 9 ,-1 , 0
       0     .06       0  197.67     .12       0  242.96     .06       0
  375.55    .045       0   389.7     .06       0   431.1    .016       0
  474.37     .08       0  504.49     .06       0  744.85     .08       0
Bank Sta=375.55,389.7
XS Rating Curve= 0 ,0
Exp/Cntr=0.3,0.1

Type RM Length L Ch R = 1 ,2588.7  ,115.2,118.5,156.9
XS GIS Cut Line= 4
     2057848.847       202740.59     2057471.243      202734.079
     2057481.616      202796.796     2057135.479      202865.156
#Sta/Elev= 30
       0 1663.92   133.5 1634.72   149.8 1630.22   188.21616.761   214.9 1607.73
  228.981604.608   244.2 1601.48   263.7 1594.41   273.5 1592.14   309.3 1589.36
   325.6 1589.51     3441586.703   367.9  1587.4   377.7 1584.38   390.4 1584.31
   393.6 1584.34   406.3 1587.89   441.2 1588.64  452.241591.266   464.1 1591.74
  482.351599.018   532.7 1628.28   568.6 1637.97   607.8 1644.57   624.2 1648.68
   640.5 1655.36   689.5 1680.26  729.131691.469   767.9 1699.75     794 1700.54
#Mann= 9 ,-1 , 0
       0     .06       0   188.2     .12       0  228.98     .06       0
     344    .016       0   377.7    .045       0   393.6    .016       0
  452.24     .08       0  482.35     .06       0  729.13     .08       0
#XS Ineff= 2 , 0
                          407.06         1589.37
Permanent Ineff=
       F       F
Bank Sta=377.7,393.6
XS Rating Curve= 0 ,0
Exp/Cntr=0.3,0.1

Type RM Length L Ch R = 1 ,2470.2  ,248.5,250.3,239.8
XS GIS Cut Line= 3
     2057804.581      202514.426     2057452.246      202633.789
     2057092.401      202678.306
#Sta/Elev= 30
       0 1632.65    32.6 1620.85    52.2 1615.16   114.2 1606.73   127.3 1603.58
  181.391600.018   215.4 1597.95   231.7 1598.39   257.8 1591.37   277.4  1591.4
  329.951586.189   352.4  1586.2  360.451583.738   362.2 1583.12     372 1582.34
  376.571583.097   388.3 1586.12     4311603.233   440.6 1607.22   456.9 1608.96
  466.631613.812   486.3 1623.18   499.4 1630.74  508.261633.764  549.851652.469
  559.821656.821   581.71666.198  613.511674.876  710.451689.189   734.6  1689.5
#Mann= 14 ,-1 , 0
       0     .12       0  181.39     .06       0  329.95    .016       0
  360.45     .08       0   362.2    .045       0  376.57     .08       0
     431    .016       0  466.63     .08       0  508.26     .06       0
  549.85     .08       0  559.82     .06       0   581.7     .08       0
  613.51     .06       0  710.45     .08       0
Bank Sta=362.2,376.57
XS Rating Curve= 0 ,0
Exp/Cntr=0.3,0.1

Type RM Length L Ch R = 1 ,2219.9  ,263.1,247.9,238.2
XS GIS Cut Line= 3
     2057752.756      202296.659     2057406.802      202389.475
     2057071.711      202602.245
#Sta/Elev= 30
       0 1672.79    55.4 1661.46    94.4 1651.72   156.3 1633.86  173.861627.287
   208.4 1607.48   231.2 1600.48   260.5 1587.69  273.591586.375  322.481584.495
  336.951581.703   348.4 1580.62   354.9 1580.45   361.5 1580.57   371.3 1582.56
  385.141589.951   404.1 1601.36   433.6 1612.57   469.7 1620.42  493.271627.579
   515.6 1627.17  527.281631.005   538.6 1636.23  562.27 1644.37  597.261657.114
  623.431664.805  632.251666.775   715.8 1683.35   735.4 1685.79   755.1 1685.18
#Mann= 14 ,-1 , 0
       0     .06       0  173.86     .12       0  273.59    .016       0
  322.48     .06       0  336.95     .12       0   348.4    .045       0
   361.5     .12       0  385.14     .08       0  493.27    .016       0
  527.28     .08       0  562.27     .06       0  597.26     .08       0
  623.43     .06       0  632.25     .08       0
#XS Ineff= 2 , 0
          294.53 1586.25
Permanent Ineff=
       F       F
Bank Sta=348.4,361.5
XS Rating Curve= 0 ,0
Exp/Cntr=0.3,0.1