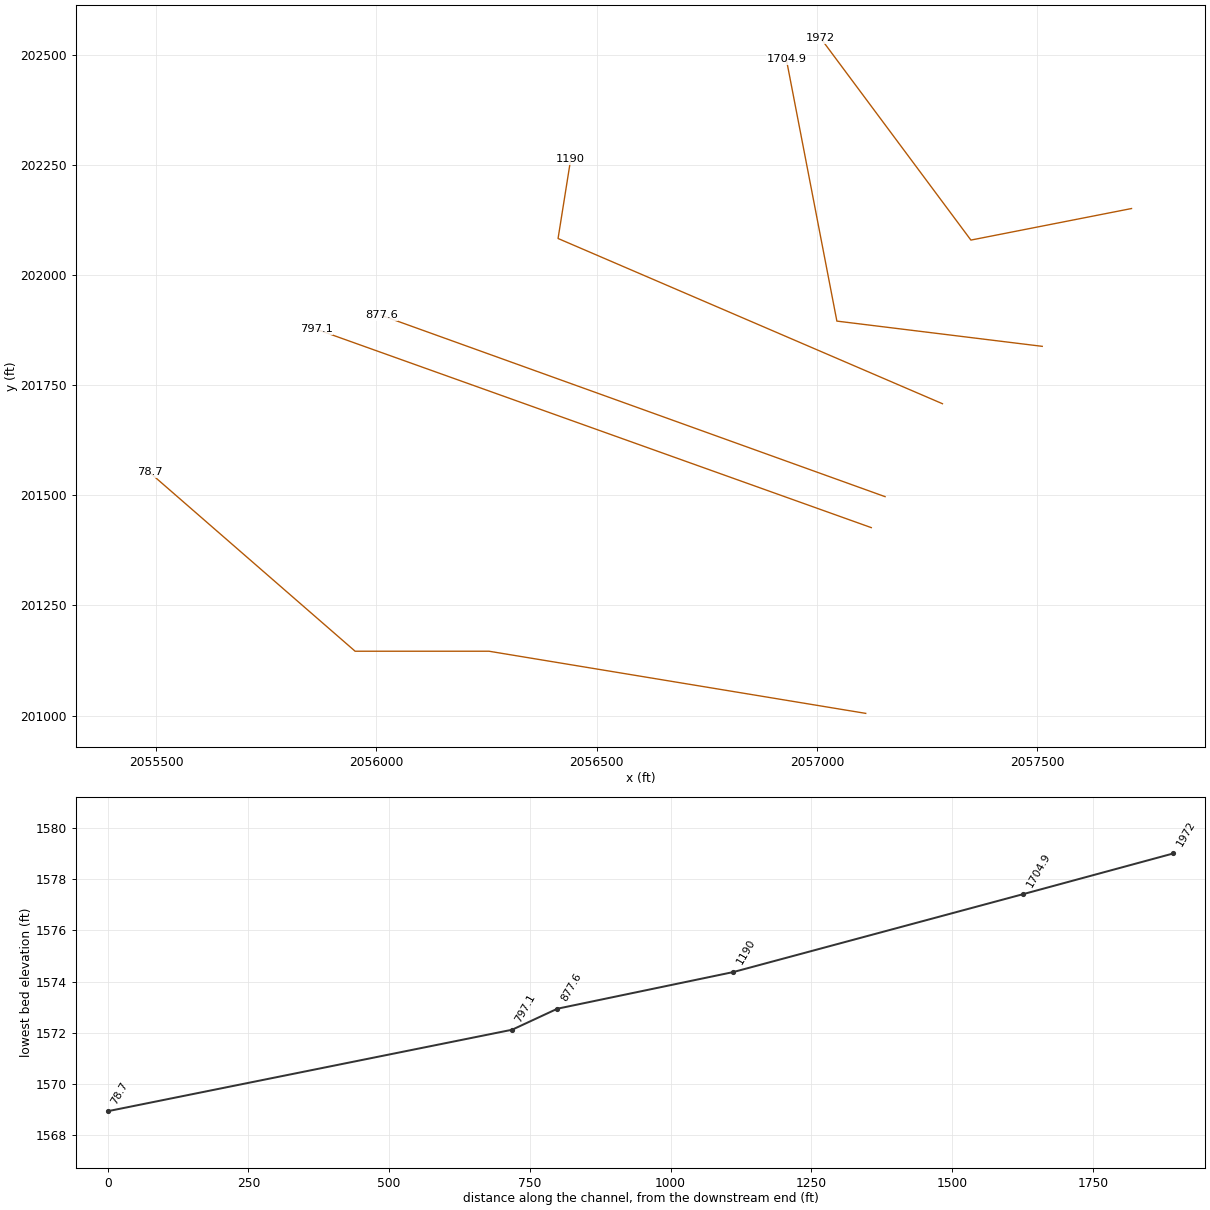
HEC-RAS study INDIANDFT.prj: INDIANDFT

--- INDIANDFT.g01 (geometry) --- (continued)

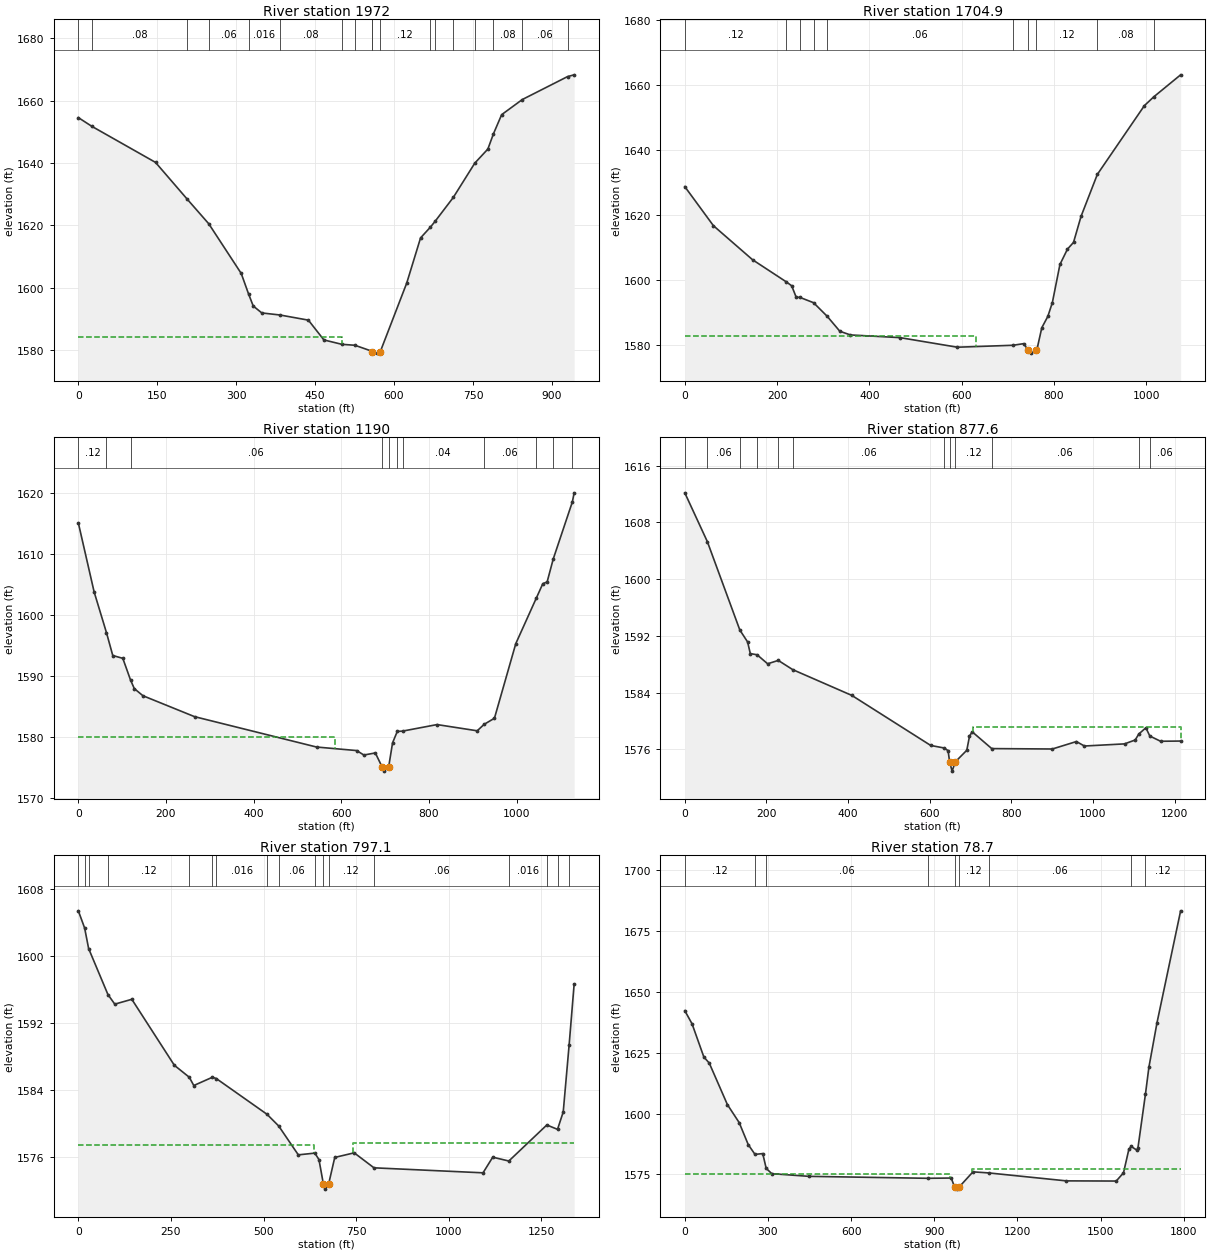
Type RM Length L Ch R = 1 ,1972    ,276.4,267.1,257.4
XS GIS Cut Line= 3
     2057714.081      202150.775     2057349.498       202079.16
     2057008.786       202537.06
#Sta/Elev= 30
       0 1654.55   25.491651.767   146.7 1640.18  207.321628.308  247.881620.492
   309.6 1604.55  323.471598.006   332.4 1594.11   348.7 1591.89  383.29 1591.23
   437.2 1589.58   466.7 1583.23  500.841581.826  525.67 1581.52  558.211579.598
   558.5  1579.5   568.4    1579  573.931579.497   624.1 1601.47   650.4 1615.96
  669.071619.411  677.831621.232   712.61628.938  753.531639.959   778.3 1644.46
  788.991649.379   804.5 1655.49  843.751660.344  929.781667.707   942.3 1668.27
#Mann= 18 ,-1 , 0
       0    .016       0   25.49     .08       0  207.32    .016       0
  247.88     .06       0  323.47    .016       0  383.29     .08       0
  500.84     .12       0  525.67     .06       0  558.21     .12       0
   558.5    .045       0  573.93     .12       0  669.07     .08       0
  677.83     .06       0   712.6     .08       0  753.53    .016       0
  788.99     .08       0  843.75     .06       0  929.78     .08       0
#XS Ineff= 2 , 0
          500.88 1584.23
Permanent Ineff=
       F       F
Bank Sta=558.5,573.93
XS Rating Curve= 0 ,0
Exp/Cntr=0.3,0.1

Type RM Length L Ch R = 1 ,1704.9  ,475.6,514.9,541.6
XS GIS Cut Line= 3
     2057511.477      201837.985     2057045.331      201895.277
     2056930.748      202489.027
#Sta/Elev= 30
       0 1628.67      62 1616.64   146.8 1606.16  219.49 1599.39   231.6 1598.14
   241.4 1594.61  249.251594.577  279.011592.933  308.771588.716   335.9 1584.15
   358.8 1583.01   466.4 1582.18   590.6 1579.23  711.331579.829   734.4 1580.33
   744.1 1578.27   750.8 1577.41   760.6 1578.26   763.8    1579   773.6 1585.23
   786.7 1588.73   796.5 1592.99   812.9 1604.71   829.2 1609.43   842.3 1611.49
   858.6  1619.5  893.941632.432   995.9  1653.6 1016.041656.283  1074.4 1663.08
#Mann= 10 ,-1 , 0
       0     .12       0  219.49     .06       0  249.25    .016       0
  279.01     .08       0  308.77     .06       0  711.33     .12       0
   744.1    .045       0   760.6     .12       0  893.94     .08       0
 1016.04    .016       0
#XS Ineff= 2 , 0
          630.34 1582.67
Permanent Ineff=
       F       F
Bank Sta=744.1,760.6
XS Rating Curve= 0 ,0
Exp/Cntr=0.3,0.1

Type RM Length L Ch R = 1 ,1190    ,310.6,312.4,313
XS GIS Cut Line= 3
     2057284.915      201707.777     2056412.519      202082.777
     2056441.165      202262.465
#Sta/Elev= 30
       0 1615.06      36 1603.76   64.221597.066    78.6 1593.32   101.5 1592.86
  119.12 1589.31   127.7  1587.9   147.4 1586.73   265.2  1583.3   543.6 1578.32
   635.2 1577.74   651.6 1577.01   677.8 1577.35   693.1 1575.07   697.4 1574.37
   708.1 1575.02   717.1 1579.01  727.871580.878   739.81580.928   818.6    1582
   910.3 1580.98  925.91 1582.03   949.6 1583.04   998.3 1595.27 1045.151602.736
    1060  1605.1  1069.8 1605.38 1083.78 1609.15 1127.351618.492  1131.5 1619.99
#Mann= 11 ,-1 , 0
       0     .12       0   64.22    .016       0  119.12     .06       0
   693.1    .045       0   708.1     .06       0  727.87     .12       0
   739.8     .04       0  925.91     .06       0 1045.15    .016       0
 1083.78     .06       0 1127.35     .12       0
#XS Ineff= 2 , 0
          586.62 1580.04
Permanent Ineff=
       F       F
Bank Sta=693.1,708.1
XS Rating Curve= 0 ,0
Exp/Cntr=0.3,0.1

Type RM Length L Ch R = 1 ,877.6   ,80.4,80.4,80.5
XS GIS Cut Line= 2
     2057154.706       201496.84     2056011.477      201908.298
#Sta/Elev= 30
       0 1612.17   55.271605.288  134.88 1592.83   153.9 1591.15   160.5 1589.51
  177.27 1589.34     203 1588.07  229.071588.546  264.481587.247   409.4 1583.61
   602.6 1576.56  635.911576.197   645.2 1575.82  648.911574.255     655 1572.94
  663.021574.255     691 1575.88   697.6 1577.84   704.1 1578.49  752.151576.116
   900.6 1576.06   959.6 1577.11   979.2 1576.48  1077.5 1576.78  1103.7 1577.33
 1112.611578.181  1129.9 1579.05 1139.491577.888  1165.9 1577.15    1215 1577.18
#Mann= 12 ,-1 , 0
       0     .12       0   55.27     .06       0  134.88     .12       0
  177.27    .016       0  229.07     .08       0  264.48     .06       0
  635.91     .12       0  648.91    .045       0  663.02     .12       0
  752.15     .06       0 1112.61    .016       0 1139.49     .06       0
#XS Ineff= 2 , 0
                          705.37         1579.23
Permanent Ineff=
       F       F
Bank Sta=648.91,663.02
XS Rating Curve= 0 ,0
Exp/Cntr=0.3,0.1

Type RM Length L Ch R = 1 ,797.1   ,709.7,718.5,722.2
XS GIS Cut Line= 2
     2057123.456      201426.527      2055863.04      201877.048
#Sta/Elev= 30
       0  1605.4   17.051603.336   27.78 1600.89      801595.381    98.4 1594.24
   144.4 1594.82   259.2 1586.93  299.471585.501   311.7 1584.51  362.01  1585.5
  372.371585.345  509.391581.068  540.761579.678   593.8 1576.22  638.541576.426
   649.6 1575.65  661.351572.777     666 1572.12   675.8 1572.75   692.2 1575.91
   744.7 1576.46  798.111574.668  1092.5 1574.07  1118.7 1575.94 1162.151575.482
 1264.71 1579.79 1293.621579.269    1309 1581.35 1324.991589.394  1338.5 1596.66
#Mann= 17 ,-1 , 0
       0     .06       0   17.05     .12       0   27.78     .06       0
      80     .12       0  299.47    .016       0  362.01     .08       0
  372.37    .016       0  509.39     .08       0  540.76     .06       0
  638.54     .12       0  661.35    .045       0   675.8     .12       0
  798.11     .06       0 1162.15    .016       0 1264.71     .08       0
 1293.62     .06       0 1324.99     .12       0
#XS Ineff= 2 , 0
          637.15 1577.36  742.62         1577.64
Permanent Ineff=
       F       F
Bank Sta=661.35,675.8
XS Rating Curve= 0 ,0
Exp/Cntr=0.3,0.1

Type RM Length L Ch R = 1 ,78.7    ,80.4,78.7,76.9
XS GIS Cut Line= 4
     2057110.783      201004.941     2056255.748         201146.
     2055951.929         201146.     2055485.349      201551.816
#Sta/Elev= 30
       0 1642.26    26.2 1636.84    68.7 1623.23    88.3 1620.71   153.7 1603.66
   196.2 1596.27   228.9 1587.22  253.281583.209   281.2 1583.54  293.651577.475
   313.9 1575.29     448 1574.19  876.251573.391   961.3  1573.5   973.4 1569.72
   980.9 1568.94   988.4 1569.64  1039.7 1576.04 1096.551575.595  1376.5 1572.33
  1556.5 1572.26  1582.7 1575.63  1602.3  1585.4 1610.591586.469  1631.7 1584.88
    1635 1586.02 1661.891607.955  1674.3 1618.97  1703.7 1637.36  1788.8 1683.27
#Mann= 9 ,-1 , 0
       0     .12       0  253.28    .016       0  293.65     .06       0
  876.25     .12       0   973.4    .045       0   988.4     .12       0
 1096.55     .06       0 1610.59    .016       0 1661.89     .12       0
#XS Ineff= 2 , 0
             958 1575.28 1037.56         1577.29
Permanent Ineff=
       F       F
Bank Sta=973.4,988.4
XS Rating Curve= 0 ,0
Exp/Cntr=0.3,0.1

Chan Stop Cuts=-1
Use User Specified Reach Order=0
Composite Channel Slope=5